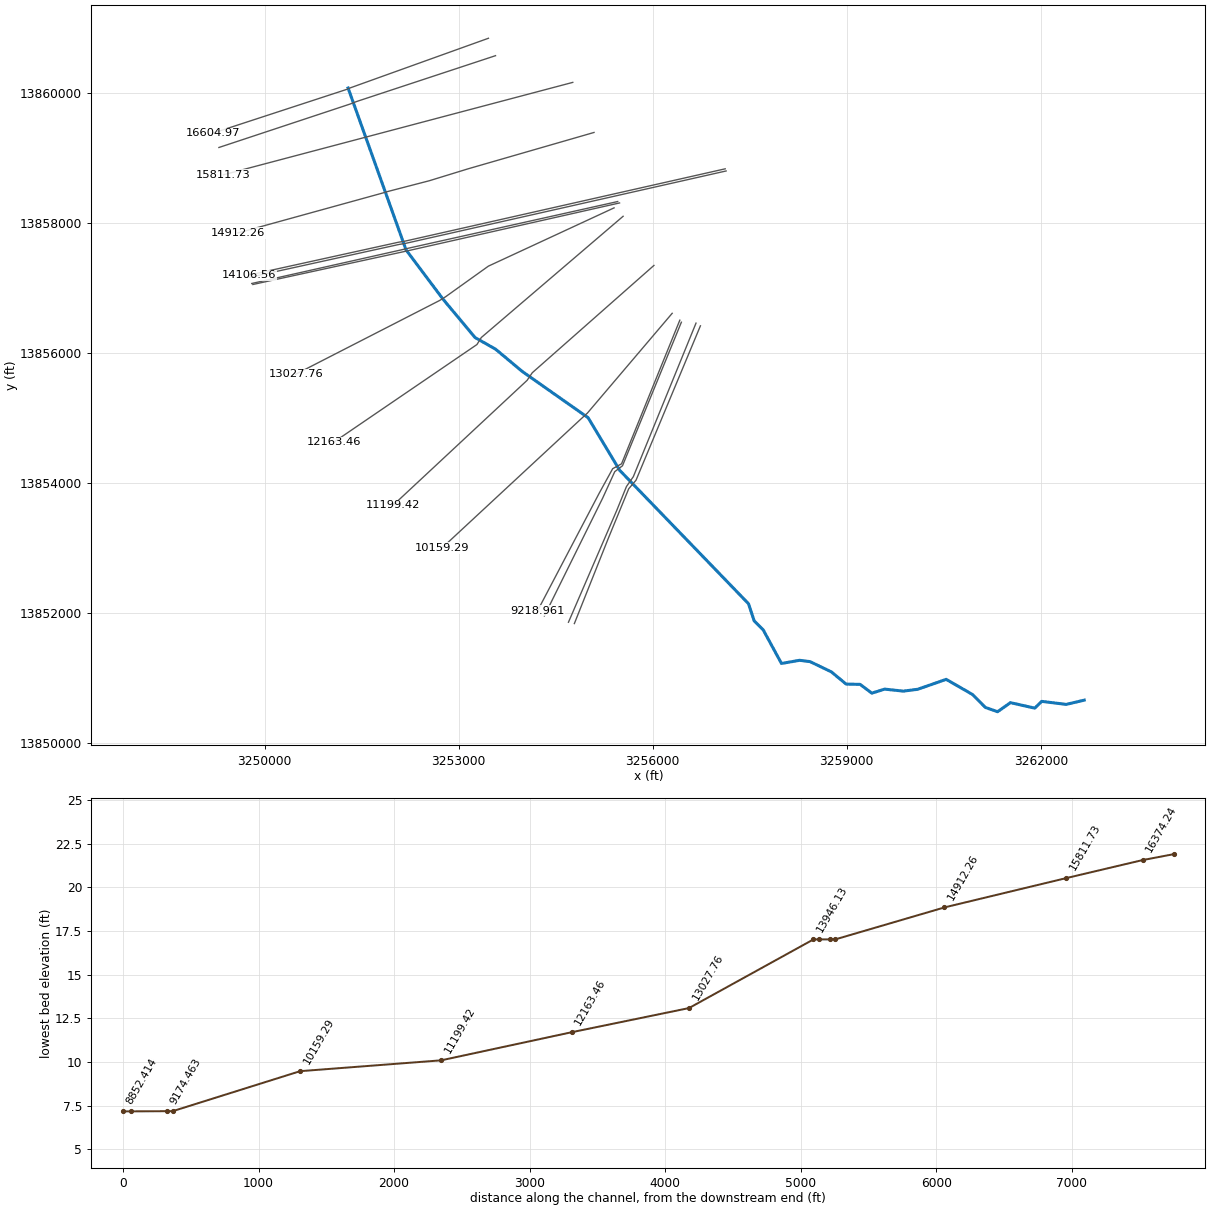
--- Q112-00-00.prj (project) ---

Proj Title=Q112-00-00
Current Plan=p01
Default Exp/Contr=.3,.1
English Units
Geom File=g04
Flow File=f01
Flow File=f02
Plan File=p04
Plan File=p01
Y Axis Title=Elevation
X Axis Title(PF)=Main Channel Distance
X Axis Title(XS)=Station
BEGIN DESCRIPTION:
Cedar Bayou Watershed
Cary Bayou
HCFCD unit Q112-00-00
Flood Hazard Model
10, 2, 1, 0.2% Event
Filename Q1120000.prj
Prepared by:  FTN Associates Ltd.   DATE:  February 2003
Reviewed by: 	 DATE:
STATUS (Final)
Flood Hazard Flows provided by DEC.
Original FIS Flows and Manning's n values  taken from 1983 FIS model unless specified otherwise.
Starting condition = normal depth slope which is based on the 5 most downstream surveyed channel sections.  RS 208 to RS 3173, change in elev = 5.74', dist = 2964.45' for a slope computation of 0.00194.  The previous HEC-2 model begins with a slope of 0.0022, which is comparable to the value computed with the recently surveyed channel data.
END DESCRIPTION:
DSS Export Rating Curves= 0
DSS Export Rating Curve Sorted= 0
DSS Export Volume Flow Curves= 0
DXF OffsetX= 0
DXF OffsetY= 0
DXF ScaleX= 1
DXF ScaleY= 10

--- Q112-00-00.p01 (plan) ---

Plan Title= Floodway
Version=Version 3.0.1  Mar 2001
Short Identifier=Floodway0607
Geom File=g04
Flow File=f02
Subcritical Flow
K Sum by GR= 0
Std Step Tol= 0.01
Critical Tol= 0.01
Num of Std Step Trials= 20
Max Error Tol= 0.3
Flow Tol Ratio= 0.001
Split Flow NTrial= 30
Split Flow Tol= 0.02
Split Flow Ratio= 0.02
Log Output Level= 0
Friction Slope Method= 1
Unsteady Friction Slope Method= 2
Parabolic Critical Depth
Global Vel Dist= 0 , 0 , 0
Global Log Level= 0
CheckData=True
Encroach Param=-1 ,0,0, 2
Encroach River=Q112-00-00
Encroach Reach=Cary Bayou
Encroach Node=16604.97
       1 1710.33 2313.86
Encroach Node=16374.24
       1    1730 2336.92
Encroach Node=15811.73
       1 2744.42 3326.18
Encroach Node=14912.26
       1    3000 3382.83
Encroach Node=14106.56
       1    3000    3400
Encroach Node=14070.51
       1    3000    3400
Encroach Node=14027.44
       1    3000    3400
Encroach Node=13984.37
       1    3000    3400
Encroach Node=13946.13
       1    3000    3400
Encroach Node=13027.76
       1 2978.77 3056.61
Encroach Node=12163.46
       1 2902.84 2980.19
Encroach Node=11199.42
       1 2526.98 2613.33
Encroach Node=10159.29
       1 2032.25  2128.1
Encroach Node=9218.961
       1  2431.4 2507.94
Encroach Node=9174.463
       1 2605.18 2681.72
Encroach Node=9042.558
       1 2600.34 2697.43
Encroach Node=8910.655
       1 2600.34 2697.43
Encroach Node=8852.414
       1  2607.4 2704.49
Encroach Node=7900.978
       1  1646.5 1734.38
Encroach Node=7863.136
       1 1546.02  1628.6
Encroach Node=7844.016
       1 1546.02 1634.43
Encroach Node=7824.900
       1 1551.85 1634.43
Encroach Node=7748.330
       1 1639.55 1727.43
Encroach Node=7152.111
       1  650.07  742.22
Encroach Node=7110.155
       1  650.07  742.22
Encroach Node=7093.615
       1  650.07  743.92
Encroach Node=7077.079
       1  651.77  743.92
Encroach Node=7036.392
       1  651.77  743.92
Encroach Node=6728.163
       1  731.94  814.01
Encroach Node=6685.249
       1  733.79  815.86
Encroach Node=6672.524
       1     730  815.86
Encroach Node=6659.798
       1  733.79  815.86
Encroach Node=6611.669
       1  733.79  815.86
Encroach Node=6326.641
       1  746.33  834.54
Encroach Node=6265.371
       1  745.19   833.4
Encroach Node=6250.821
       1  745.19  835.39
Encroach Node=6236.272
       1  747.18  835.39
Encroach Node=6185.255
       1  739.78  827.99
Encroach Node=6028.051
       1  901.63  999.61
Encroach Node=5162.542
       1 1174.25 1298.94
Encroach Node=4086.435
       1 1250.52 1394.88
Encroach Node=3173.282
       1  1296.4 1418.19
Encroach Node=3122.691
       1  1325.8 1447.59
Encroach Node=3083.351
       1    1313 1447.59
Encroach Node=3044.014
       1 1319.05 1440.84
Encroach Node=2970.430
       1 1316.22 1438.01
Encroach Node=2200.530
       1    1312    1417
Encroach Node=1807.453
       1    1468    1558
Encroach Node=1111.880
       1    1456    1575
Encroach Node=208.834
       1    1400    1470
Encroach Reach=Q112-00-00_0002
Encroach Node=16604.97
       1 1710.33 2313.86
Encroach Node=16374.24
       1    1730 2336.92
Encroach Node=15811.73
       1 2744.42 3326.18
Encroach Node=14912.26
       1    3000 3382.83
Encroach Node=14106.56
       1    3000    3400
Encroach Node=14070.51
       1    3000    3400
Encroach Node=14027.44
       1    3000    3400
Encroach Node=13984.37
       1    3000    3400
Encroach Node=13946.13
       1    3000    3400
Encroach Node=13027.76
       1 2978.77 3056.61
Encroach Node=12163.46
       1 2902.84 2980.19
Encroach Node=11199.42
       1 2526.98 2613.33
Encroach Node=10159.29
       1 2032.25  2128.1
Encroach Node=9218.961
       1  2431.4 2507.94
Encroach Node=9174.463
       1 2605.18 2681.72
Encroach Node=9042.558
       1 2600.34 2697.43
Encroach Node=8910.655
       1 2600.34 2697.43
Encroach Node=8852.414
       1  2607.4 2704.49
Encroach Node=7900.978
       1  1646.5 1734.38
Encroach Node=7863.136
       1 1546.02  1628.6
Encroach Node=7844.016
       1 1546.02 1634.43
Encroach Node=7824.900
       1 1551.85 1634.43
Encroach Node=7748.330
       1 1639.55 1727.43
Encroach Node=7152.111
       1  650.07  742.22
Encroach Node=7110.155
       1  650.07  742.22
Encroach Node=7093.615
       1  650.07  743.92
Encroach Node=7077.079
       1  651.77  743.92
Encroach Node=7036.392
       1  651.77  743.92
Encroach Node=6728.163
       1  731.94  814.01
Encroach Node=6685.249
       1  733.79  815.86
Encroach Node=6672.524
       1     730  815.86
Encroach Node=6659.798
       1  733.79  815.86
Encroach Node=6611.669
       1  733.79  815.86
Encroach Node=6326.641
       1  746.33  834.54
Encroach Node=6265.371
       1  745.19   833.4
Encroach Node=6250.821
       1  745.19  835.39
Encroach Node=6236.272
       1  747.18  835.39
Encroach Node=6185.255
       1  739.78  827.99
Encroach Node=6028.051
       1  901.63  999.61
Encroach Node=5162.542
       1 1174.25 1298.94
Encroach Node=4086.435
       1 1250.52 1394.88
Encroach Node=3173.282
       1  1296.4 1418.19
Encroach Node=3122.691
       1  1325.8 1447.59
Encroach Node=3083.351
       1    1313 1447.59
Encroach Node=3044.014
       1 1319.05 1440.84
Encroach Node=2970.430
       1 1316.22 1438.01
Encroach Node=2200.530
       1    1312    1417
Encroach Node=1807.453
       1    1468    1558
Encroach Node=1111.880
       1    1456    1575
Encroach Node=208.834
       1    1400    1470
Computation Interval=1HOUR
Output Interval=1HOUR
Run HTab= 0
Run UNet= 0
Run PostProcess= 0
UNET Theta= 1
UNET ZTol= 0.02
UNET ZSATol= 0.1
UNET MxIter= 20
UNET MaxInSteps= 20
UNET DtIC= 0
UNET DtMin= 0
UNET MaxCRTS= 20
UNET WFStab= 2
UNET SFStab= 1
UNET WFX= 1
UNET SFX= 1
UNET Convert EG Bridges=-1
UNET Use Existing IB Tables=-1
Instantaneous Interval=1HOUR
Write IC File= 0
Write Velocity= 0
Write Detailed= 0

--- Q112-00-00.p04 (plan) ---

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Plan Title=FEMA Effective June 2007
Short Identifier=FEMAeff0607
Geom File=g04
Flow File=f01
Encroach Param=-1 ,0,0, 0

--- Q112-00-00.f02 (steady flow) ---

Flow Title=Floodway
Version=Version 3.0.1  Mar 2001
Number of Profiles= 2
Profile Names=1PCT_100yr,Floodway_100yrFW
River Rch & RM=Q112-00-00,Q112-00-00_0002 ,16604.97
     920     920
River Rch & RM=Q112-00-00,Q112-00-00_0002 ,16374.24
     967     967
River Rch & RM=Q112-00-00,Q112-00-00_0002 ,15811.73
    1047    1047
River Rch & RM=Q112-00-00,Q112-00-00_0002 ,14912.26
    1124    1124
River Rch & RM=Q112-00-00,Q112-00-00_0002 ,14106.56
    1140    1140
River Rch & RM=Q112-00-00,Q112-00-00_0002 ,13946.13
    1237    1237
River Rch & RM=Q112-00-00,Q112-00-00_0002 ,13027.76
    1335    1335
River Rch & RM=Q112-00-00,Q112-00-00_0002 ,12163.46
    1454    1454
River Rch & RM=Q112-00-00,Q112-00-00_0002 ,11199.42
    1594    1594
River Rch & RM=Q112-00-00,Q112-00-00_0002 ,10159.29
    1732    1732
River Rch & RM=Q112-00-00,Q112-00-00_0002 ,9218.961
    1780    1780
River Rch & RM=Q112-00-00,Q112-00-00_0002 ,8910.655
    1790    1790
River Rch & RM=Q112-00-00,Q112-00-00_0002 ,8852.414
    1962    1962
River Rch & RM=Q112-00-00,Q112-00-00_0002 ,7900.978
    1991    1991
River Rch & RM=Q112-00-00,Q112-00-00_0002 ,7748.330
    2109    2109
River Rch & RM=Q112-00-00,Q112-00-00_0002 ,7152.111
    2222    2222
River Rch & RM=Q112-00-00,Q112-00-00_0002 ,6611.669
    2284    2284
River Rch & RM=Q112-00-00,Q112-00-00_0002 ,6326.641
    2351    2351
River Rch & RM=Q112-00-00,Q112-00-00_0002 ,6028.051
    2556    2556
River Rch & RM=Q112-00-00,Q112-00-00_0002 ,5162.542
    2836    2836
River Rch & RM=Q112-00-00,Q112-00-00_0002 ,4086.435
    3097    3097
River Rch & RM=Q112-00-00,Q112-00-00_0002 ,3173.282
    3158    3158
River Rch & RM=Q112-00-00,Q112-00-00_0002 ,2970.430
    3402    3402
River Rch & RM=Q112-00-00,Q112-00-00_0002 ,2200.530
    3534    3534
River Rch & RM=Q112-00-00,Q112-00-00_0002 ,1807.453
    3779    3779
River Rch & RM=Q112-00-00,Q112-00-00_0002 ,1111.880
    4123    4123
Boundary for River Rch & Prof#=Q112-00-00,Q112-00-00_0002 , 1
Up Type= 0
Dn Type= 3
Dn Slope=.00194
DSS Import GetInterval= 0
DSS Import GetPeak= 0
DSS Import FillOption= 0

--- Q112-00-00.f01 (steady flow) ---

Flow Title=FEMA Effective June 2007
Version=Version 3.0.1  Mar 2001
Number of Profiles= 4
Profile Names=10PCT_10yr,2PCT_50yr,1PCT_100yr,0.2PCT_500yr
River Rch & RM=Q112-00-00,Q112-00-00_0002 ,16604.97
     514     781     920    1332
River Rch & RM=Q112-00-00,Q112-00-00_0002 ,16374.24
     541     820     967    1400
River Rch & RM=Q112-00-00,Q112-00-00_0002 ,15811.73
     587     888    1047    1518
River Rch & RM=Q112-00-00,Q112-00-00_0002 ,14912.26
     631     954    1124    1631
River Rch & RM=Q112-00-00,Q112-00-00_0002 ,14106.56
     641     967    1140    1654
River Rch & RM=Q112-00-00,Q112-00-00_0002 ,13946.13
     696    1049    1237    1796
River Rch & RM=Q112-00-00,Q112-00-00_0002 ,13027.76
     753    1132    1335    1940
River Rch & RM=Q112-00-00,Q112-00-00_0002 ,12163.46
     821    1233    1454    2114
River Rch & RM=Q112-00-00,Q112-00-00_0002 ,11199.42
     902    1352    1594    2320
River Rch & RM=Q112-00-00,Q112-00-00_0002 ,10159.29
     982    1469    1732    2523
River Rch & RM=Q112-00-00,Q112-00-00_0002 ,9218.961
    1010    1509    1780    2593
River Rch & RM=Q112-00-00,Q112-00-00_0002 ,8910.655
    1016    1518    1790    2608
River Rch & RM=Q112-00-00,Q112-00-00_0002 ,8852.414
    1116    1666    1962    2852
River Rch & RM=Q112-00-00,Q112-00-00_0002 ,7900.978
    1133    1691    1991    2893
River Rch & RM=Q112-00-00,Q112-00-00_0002 ,7748.330
    1202    1792    2109    3060
River Rch & RM=Q112-00-00,Q112-00-00_0002 ,7152.111
    1269    1890    2222    3220
River Rch & RM=Q112-00-00,Q112-00-00_0002 ,6611.669
    1305    1943    2284    3307
River Rch & RM=Q112-00-00,Q112-00-00_0002 ,6326.641
    1344    2001    2351    3402
River Rch & RM=Q112-00-00,Q112-00-00_0002 ,6028.051
    1465    2177    2556    3690
River Rch & RM=Q112-00-00,Q112-00-00_0002 ,5162.542
    1630    2419    2836    4084
River Rch & RM=Q112-00-00,Q112-00-00_0002 ,4086.435
    1785    2645    3097    4450
River Rch & RM=Q112-00-00,Q112-00-00_0002 ,3173.282
    1821    2698    3158    4536
River Rch & RM=Q112-00-00,Q112-00-00_0002 ,2970.430
    1966    2909    3402    4877
River Rch & RM=Q112-00-00,Q112-00-00_0002 ,2200.530
    2044    3022    3534    5061
River Rch & RM=Q112-00-00,Q112-00-00_0002 ,1807.453
    2190    3235    3779    5403
River Rch & RM=Q112-00-00,Q112-00-00_0002 ,1111.880
    2395    3534    4123    5883
Boundary for River Rch & Prof#=Q112-00-00,Q112-00-00_0002 , 1
Up Type= 0
Dn Type= 3
Dn Slope=.00194
DSS Import GetInterval= 0
DSS Import GetPeak= 0
DSS Import FillOption= 0

--- Q112-00-00.g04 (geometry) ---

Geom Title=Q112-00-00 June 2007
Version=Version 3.0.1  Mar 2001

River Reach=Q112-00-00      ,Q112-00-00_0002
Reach XY= 30
     3251292.208    13860075.384       3252187.8    13857585.107
     3252764.885    13856819.836     3253254.839    13856236.046
     3253571.868    13856057.089     3253984.744     13855713.92
     3255002.186    13855002.112     3255490.406    13854192.856
     3257482.119    13852138.796      3257568.83    13851875.951
     3257708.664    13851737.315      3257990.84     13851220.55
     3258272.425    13851269.033     3258433.554    13851248.444
     3258762.077    13851090.896     3258990.856    13850902.851
     3259206.971    13850898.437     3259387.645    13850763.439
     3259585.369    13850825.772     3259873.865    13850794.599
     3260095.834    13850822.784     3260537.127    13850975.908
     3260945.981     13850741.32     3261142.305    13850543.954
     3261331.183    13850477.713     3261529.909    13850617.357
     3261906.471    13850532.858     3262012.663    13850636.968
     3262391.947    13850590.503      3262670.64    13850655.708

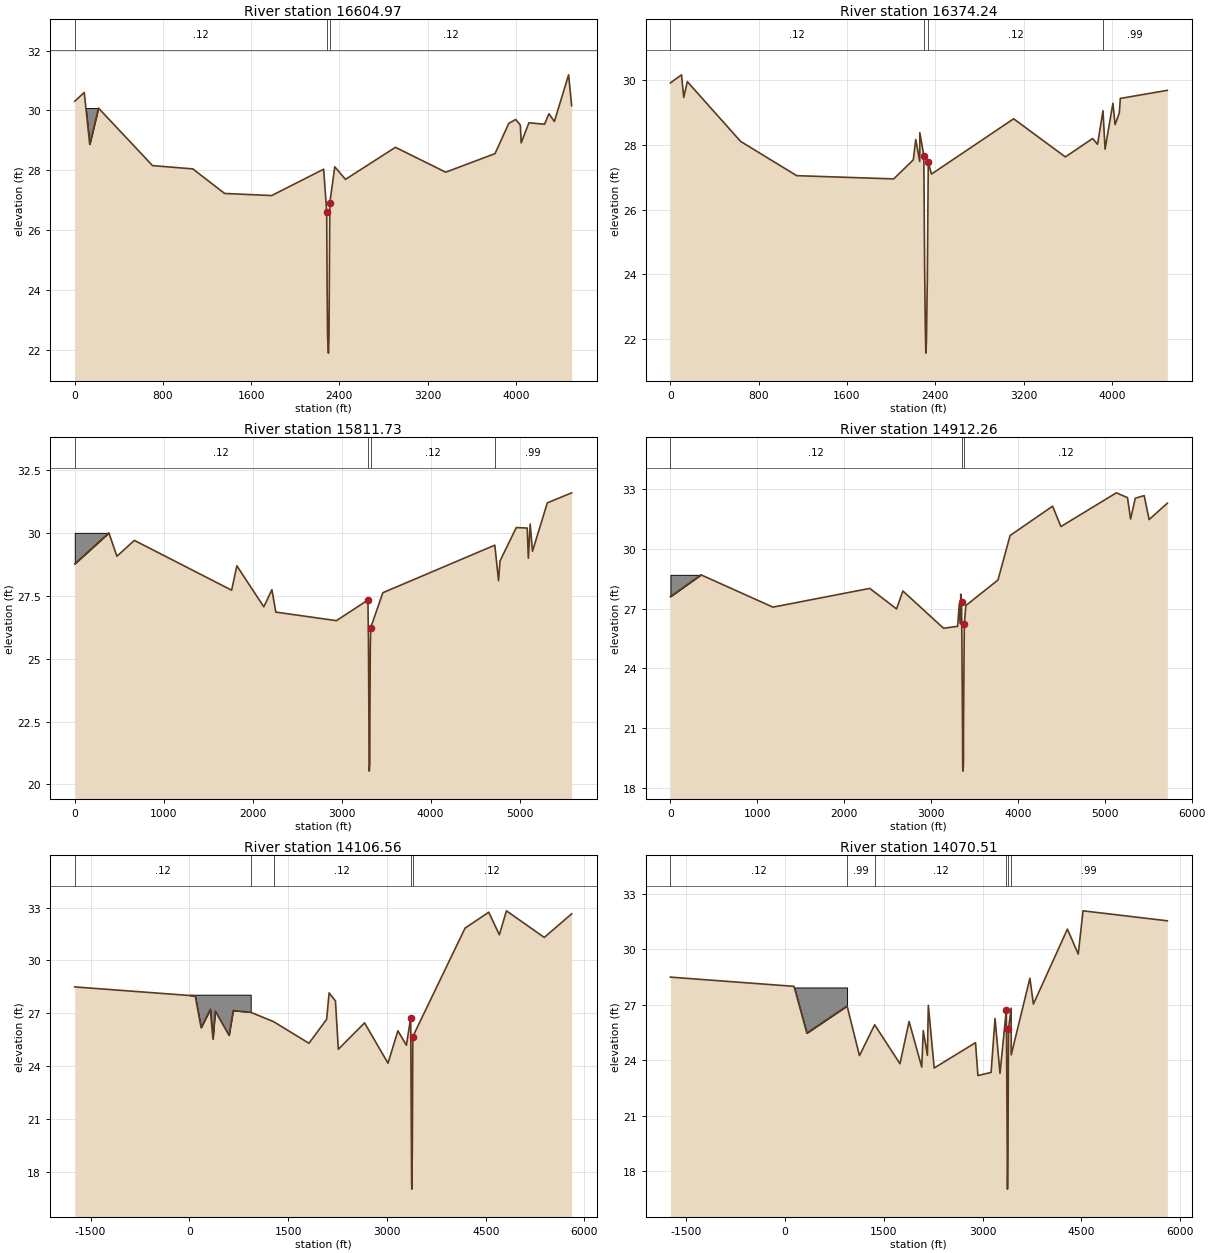
Type RM Length L Ch R = 1 ,16604.97,245.77,230.74,230.74
BEGIN DESCRIPTION:
434v2
Bank Station offset =      2699
block added in LOB & ROB to eliminate flow in offline channels
END DESCRIPTION:
XS GIS Cut Line= 4
     3253461.429    13860842.008     3251333.455    13860081.311
     3251256.507    13860050.455     3249197.897    13859380.225
#Sta/Elev= 30
       0   30.31   85.99    30.6  135.77   28.87  215.25   30.08  705.34   28.16
 1071.19   28.05 1359.36   27.23 1786.46   27.16 2257.98   28.04 2285.42   26.62
 2289.22   24.16 2293.49   22.46 2301.26    21.9 2306.35   22.42 2313.86   26.92
 2358.87   28.12 2455.58    27.7 2909.07   28.77  3365.2   27.94 3812.58   28.56
 3937.27   29.57 4000.74    29.7  4042.3   29.51 4049.86   28.92 4120.28   29.59
 4261.82   29.54 4301.82   29.89 4350.91   29.63 4479.96   31.19 4507.72   30.16
#Mann= 3 , 0 , 0
       0     .12       0 2285.42     .06       0 2313.86     .12       0
#Block Obstruct= 2 , 0
       0  215.25   30.08 4010.76       0   29.71
Bank Sta=2285.42,2313.86
XS Rating Curve= 0
Exp/Cntr=.3,.1

Type RM Length L Ch R = 1 ,16374.24,605.53,562.51,549.74
BEGIN DESCRIPTION:
434v3
Bank Station offset =      2685
END DESCRIPTION:
XS GIS Cut Line= 4
     3253571.062    13860574.014     3251424.332    13859868.708
     3251325.676    13859830.519     3249295.349    13859160.958
#Sta/Elev= 30
       0   29.92  100.61   30.17  120.74   29.47  153.12   29.96  636.42   28.11
 1144.88   27.05 2023.97   26.95 2201.21   27.54 2223.46   28.17 2259.63   27.49
  2260.4   28.38 2296.68   27.67 2303.68   24.29 2309.67   22.49 2314.71   21.56
 2320.19   21.92 2328.43   23.85 2336.92   27.46 2366.17    27.1 3110.65   28.81
  3579.3   27.63 3826.45    28.2 3870.92   28.02 3920.54   29.06 3939.12   27.87
 4010.26   29.29 4030.14   28.63 4068.39   28.99 4077.52   29.44  4503.3   29.69
#Mann= 4 ,-1 , 0
       0     .12       0 2296.68     .06       0 2336.92     .12       0
 3920.54     .99       0
Bank Sta=2296.68,2336.92
XS Rating Curve= 0
Exp/Cntr=.3,.1

Type RM Length L Ch R = 1 ,15811.73,911.61,899.47,919.75
BEGIN DESCRIPTION:
Copy of 434v4. Channel inverts adjusted based on slope.
Bank Station offset =      1690
Blocked small depression on far LOB.
LOB and RB reachlengths greater than channel reach length due to cross section orientation
END DESCRIPTION:
XS GIS Cut Line= 2
     3254764.889    13860162.899     3249364.161    13858740.485
#Sta/Elev= 30
       0   28.77  383.41      30  473.86   29.07  669.77    29.7 1763.34   27.72
 1821.91   28.69 2124.93   27.06 2215.75   27.74  2259.7   26.85 2941.18   26.51
 3295.09   27.33 3300.83   25.77 3306.37   22.43 3307.53   20.87  3310.3   20.53
 3316.44   20.82 3317.04   22.47 3321.63   25.46 3326.18   26.23 3462.48   27.62
 4721.04   29.51 4763.24    28.1  4779.3   28.88  4962.7   30.21 5085.24   30.19
 5098.31   28.99  5118.6   30.35 5144.85   29.27 5311.36   31.19  5584.9   31.59
#Mann= 4 ,-1 , 0
       0     .12       0 3295.09     .06       0 3326.18     .12       0
 4721.04     .99       0
#Block Obstruct= 2 , 0
       0   383.4      30               0
Bank Sta=3295.09,3326.18
XS Rating Curve= 0
Exp/Cntr=.3,.1

Type RM Length L Ch R = 1 ,14912.26,817.9,805.71,794.83
BEGIN DESCRIPTION:
434v4
Bank Station offset =      1633
Blocked small depression on far LOB.
END DESCRIPTION:
XS GIS Cut Line= 6
     3255093.752    13859392.407     3253144.709    13858832.057
     3252547.815    13858649.334     3251882.656    13858477.715
     3251835.395    13858462.754     3249587.705    13857845.354
#Sta/Elev= 30
       0    27.6  352.14   28.69 1180.11   27.07 2294.83   28.01 2603.19   26.98
 2675.75   27.88  3144.7   26.01 3306.45   26.11  3324.7   27.22 3339.17   26.23
 3341.77   27.72 3351.74   27.33 3363.02   20.75 3364.18   19.19 3366.95   18.85
 3373.09   19.14 3373.69   20.79 3382.83   26.23 3400.93   27.15 3770.43   28.43
 3909.88   30.66 4399.04   32.13 4495.12   31.11 5133.17    32.8 5261.32   32.56
 5297.08   31.49 5350.94   32.53 5453.46   32.66 5510.25   31.46 5719.69   32.28
#Mann= 3 ,-1 , 0
       0     .12       0 3351.74     .06       0 3382.83     .12       0
#Block Obstruct= 2 , 0
       0  352.14   28.69               0
Bank Sta=3351.74,3382.83
XS Rating Curve= 0
Exp/Cntr=.3,.1

Type RM Length L Ch R = 1 ,14106.56,37.16,36.04,35.47
BEGIN DESCRIPTION:
434s1u, East Archer Road.  XS 4/4.  Blocked far LOB - based on contours, drainage will drain to further LOB and enter Cary channel further d/s.  Set ineffective on LOB based on expansion of 1% chance flow width from d/s RS 13027 at ~ 1:1 ratio.
Bank Station offset =      1622
XS extended on LOB using elevations from tin.
END DESCRIPTION:
XS GIS Cut Line= 5
  3257121.10685713858832.7631729      3255423.52    13858450.927
      3252168.65    13857718.813     3252071.018    13857703.051
      3249755.75     13857195.85
#Sta/Elev= 30
   -1740    28.5   89.01   27.99  178.16   26.19  317.43   27.23  358.75   25.54
     393   27.13  602.74   25.75  665.08   27.16  931.52   27.06 1278.53   26.53
 1816.23    25.3 2084.63   26.66 2122.57   28.16 2218.66    27.7 2262.35   24.96
  2660.5   26.46  3016.5   24.17 3166.98   26.01  3295.6   25.19 3361.24   26.74
 3375.39   17.42 3378.32   17.02 3386.13   19.33 3393.34   25.68 4186.94   31.84
 4546.46   32.74 4707.64   31.46 4814.95   32.82  5389.7   31.31 5805.26   32.65
#Mann= 5 ,-1 , 0
   -1740     .12       0  931.52     .99       0 1278.53     .12       0
 3361.24     .06       0 3393.34     .12       0
#Block Obstruct= 2 , 0
       0  931.52   28.06               0
Bank Sta=3361.24,3393.34
XS Rating Curve= 0
Exp/Cntr=.5,.3

Type RM Length L Ch R = 1 ,14070.51,86.14,86.14,94.9
BEGIN DESCRIPTION:
Copy of 434s1u, East Archer Road.  XS 3/4.  Blocked far LOB - based on contours, drainage will drain to further LOB and enter Cary channel further d/s.  Set ineffective on LOB based on expansion of 1% chance flow width from d/s RS 13027 at ~ 1:1 ratio. Similarly on ROB, due to high road elevation on near ROB.  Adjust elevations as needed.
Bank Station offset =      1622
XS extended using elevations from tin.
END DESCRIPTION:
XS GIS Cut Line= 5
 3257135.539831913858799.8002846     3255437.953    13858417.964
     3252183.084     13857685.85     3252085.451    13857670.088
     3249770.184    13857162.887
#Sta/Elev= 30
   -1740    28.5  137.07      28  331.33   25.47  942.54   26.94  1130.8   24.25
 1361.44   25.92 1745.77   23.81 1884.18    26.1 2076.37   23.63 2099.42    25.6
 2162.32   24.27  2176.3   26.97 2265.47   23.58 2892.92   24.95 2929.66   23.17
 3129.53   23.34 3189.27   26.26 3264.58   23.29 3361.24   26.74 3378.32   17.02
 3386.13   19.33 3393.34   25.68 3433.92   26.82 3435.09   24.29 3718.65   28.44
 3771.85   27.04 4288.29    31.1 4452.74   29.75 4525.62   32.09 5805.26   31.55
#Mann= 6 ,-1 , 0
   -1740     .12       0  942.54     .99       0 1361.44     .12       0
 3361.24     .06       0 3393.34     .12       0 3433.92     .99       0
#XS Ineff= 2 , 0
       0    3356    25.7    3398       0    25.7
Permanent Ineff=
       F       F
#Block Obstruct= 2 , 0
       0  942.54   27.94               0
Bank Sta=3361.24,3393.34
XS Rating Curve= 0
Exp/Cntr=.5,.3

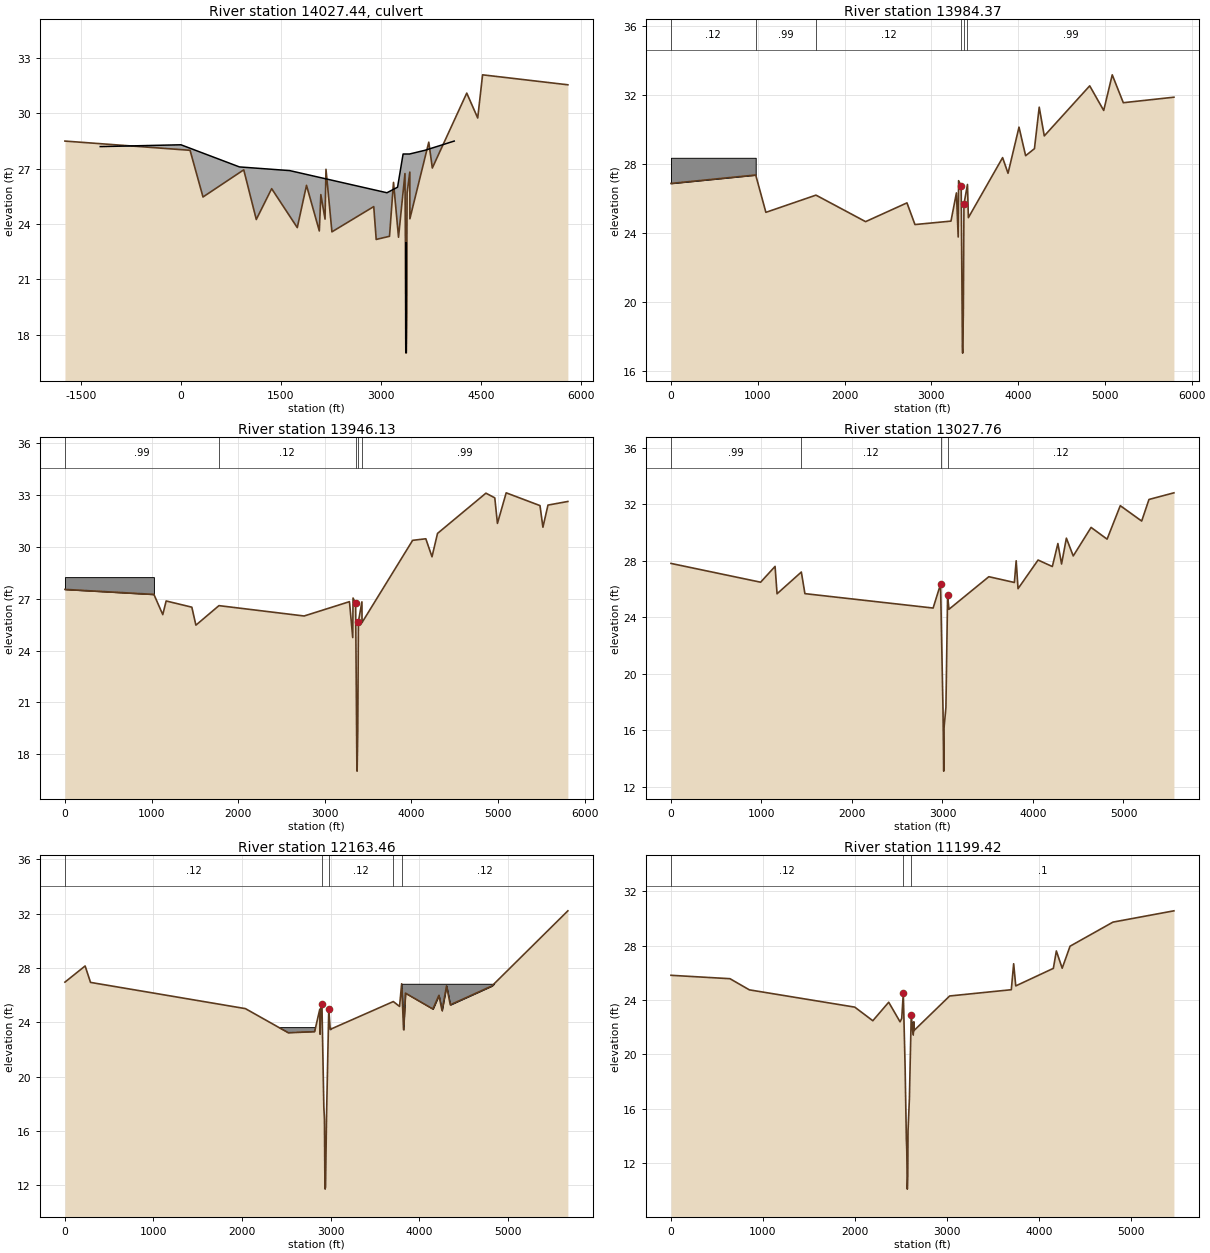
Type RM Length L Ch R = 2 ,14027.44,,,
BEGIN DESCRIPTION:
434s1- East Archer Road.
Shift the centerlines: US
included extra rway elevations from TIN
see shape file "addtl_rdpts"
END DESCRIPTION:
Bridge Culvert--1,0,0,-1, 0
Deck Dist Width WeirC Skew NumUp NumDn MinLoCord MaxHiCord MaxSubmerge Is_Ogee
31,23.5,2.6,0, 13, 13, , , .8, 0, 0,0,,
   -1210       0     878    1633    3091    3250 3333.22 3359.29    3378 3400.27
 3429.77    3660    4100
    28.2    28.3    27.1    26.9    25.7      26    27.8    27.8    27.8    27.8
    27.8      28    28.5
                                                                                
                        
       0     861    1616    3074    3233 3316.22 3342.29    3361 3383.27 3412.77
    3640    3900    4300
    28.3    27.1    26.9    25.7      26    27.8    27.8    27.8    27.8    27.8
      28    28.5    28.5
                                                                                
                        
BR Coef=-1 , 0 , 0 ,, 0 ,,,.8,0,,0,
WSPro=,,,, 1 ,,,, 0 ,,,, 0 ,,,,-1 ,-1 ,-1 , 0 , 0 , 0 , 0 , 0
Multiple Barrel Culv=1,6,,62,.013,.5,1,1,1,17.01,16.46, 2,Culvert #1  , 0 ,12
 3373.06 3356.76 3382.58 3365.49
Culvert Bottom n=.013
BC Design=,, 0 ,, 0 ,,,,,,

Type RM Length L Ch R = 1 ,13984.37,38.24,38.24,36.51
BEGIN DESCRIPTION:
Copy of 434s1u, East Archer Road.  XS 2/4.  Blocked far LOB - based on contours, drainage will drain to further LOB and enter Cary channel further d/s.  Set ineffective on LOB based on expansion of 1% chance flow width from d/s RS 13027 at ~ 1:1 ratio. Similarly on ROB, due to high road elevation on near ROB.  Adjust elevations as needed.
Bank Station offset =      1639
END DESCRIPTION:
XS GIS Cut Line= 4
     3255459.498    13858329.297     3252216.642    13857609.288
     3252119.765    13857586.626     3249802.644       13857068.
#Sta/Elev= 30
       0   26.88  976.38   27.37 1093.73    25.2 1670.86    26.2 2242.62   24.66
 2719.44   25.75 2811.64   24.49  3226.5   24.69 3289.48   26.33 3309.75   23.77
 3314.41   27.04 3344.16   26.74 3358.31   17.42 3361.24   17.02 3369.05   19.33
 3376.26   25.68 3416.84   26.82 3427.07   24.89 3821.68   28.38 3884.04   27.47
 4010.61   30.15 4086.91   28.49 4188.56    28.9 4243.47   31.31 4301.87   29.64
 4825.28   32.55 4986.57   31.12 5084.98   33.19 5212.51   31.57 5795.77   31.89
#Mann= 6 ,-1 , 0
       0     .12       0  976.38     .99       0 1670.86     .12       0
 3344.16     .06       0 3376.26     .12       0 3416.84     .99       0
#XS Ineff= 2 , 0
       0    3340    24.2    3380       0    24.2
Permanent Ineff=
       F       F
#Block Obstruct= 2 , 0
       0  976.38   28.37               0
Bank Sta=3344.16,3376.26
XS Rating Curve= 0
Exp/Cntr=.5,.3

Type RM Length L Ch R = 1 ,13946.13,877.74,918.36,961.86
BEGIN DESCRIPTION:
Copy of 434s1u, East Archer Road.  XS 1/4.  Adjust elevations as needed.  Blocked far LOB - based on contours, drainage will drain to further LOB and enter Cary channel further d/s.  Set ineffective on LOB based on expansion of 1% chance flow width from d/s RS 13027 at ~ 1:1 ratio.  Similarly on ROB, due to high road elevation on near ROB.
Bank Station offset =      1628
END DESCRIPTION:
XS GIS Cut Line= 4
     3255488.091    13858307.613     3252233.221      13857575.5
     3252134.839    13857554.157     3249820.322    13857052.536
#Sta/Elev= 30
       0   27.54 1027.04   27.25 1129.25   26.08 1168.29   26.87 1464.77   26.51
 1511.66   25.47 1777.82    26.6 2760.78      26 3284.14   26.83 3321.97   24.75
  3325.6   27.04 3355.35   26.74  3369.5   17.42 3372.43   17.02 3380.24   19.33
 3387.45   25.68 3428.03   26.82 3429.19   25.62 4013.41   30.38 4165.53   30.47
  4236.8   29.43 4300.57   30.78  4859.1   33.11 4961.59   32.84 4992.19   31.36
 5093.11   33.13 5483.43   32.39 5517.11   31.14 5575.52   32.42 5805.11   32.63
#Mann= 5 ,-1 , 0
       0     .99       0 1777.82     .12       0 3355.35     .06       0
 3387.45     .12       0 3428.03     .99       0
#Block Obstruct= 2 , 0
       0 1027.04   28.25               0
Bank Sta=3355.35,3387.45
XS Rating Curve= 0
Exp/Cntr=.3,.1

Type RM Length L Ch R = 1 ,13027.76,840.03,864.3,910.9
BEGIN DESCRIPTION:
434v5
Bank Station offset =      1986
see note:  RS12163
END DESCRIPTION:
XS GIS Cut Line= 5
     3255403.598    13858231.786     3253461.216    13857335.303
     3252797.944    13856863.012     3252706.048    13856806.218
     3250482.898    13855671.827
#Sta/Elev= 30
       0    27.8  990.44   26.47 1150.13   27.59 1172.16   25.65 1440.52   27.19
 1479.98   25.66 2896.61   24.64 2978.77   26.33 3005.81   17.43 3013.81   13.09
  3016.9   16.14  3037.9   17.59 3056.61   25.54 3071.34   24.55 3512.45   26.86
 3794.58   26.45 3814.38   27.99 3834.84   26.01  4056.4   28.04 4213.96   27.58
 4275.37   29.21 4315.91   27.76 4369.16   29.59 4445.03   28.33 4642.02   30.35
  4818.9   29.52 4964.72   31.89 5201.26    30.8 5281.76   32.33  5557.4    32.8
#Mann= 4 ,-1 , 0
       0     .99       0 1440.52     .12       0 2978.77     .06       0
 3056.61     .12       0
#Block Obstruct= 2 , 0
       0                 3814.38       0   27.99
Bank Sta=2978.77,3056.61
XS Rating Curve= 0
Exp/Cntr=.3,.1

Type RM Length L Ch R = 1 ,12163.46,989.55,964.04,948.56
BEGIN DESCRIPTION:
434v6
Bank Station offset =      2061
the right overbank is blocked due to the presence of roads; the areas could also have been blocked in subsequent cross sections (RS10159-13027), however there were no low flowage areas (mbb).  The near lob is blocked low as the 1% chance flow cannot enter this area based on ground tin data.
END DESCRIPTION:
XS GIS Cut Line= 4
     3255543.051    13858102.294     3253351.107    13856236.536
     3253283.941    13856128.781     3251070.593     13854625.93
#Sta/Elev= 30
       0   26.95  228.05   28.14  289.08   26.93 2038.39      25 2523.42   23.22
 2820.32    23.3 2878.78   24.96 2882.31   23.12  2889.2   24.93 2902.84   25.36
 2924.43   17.75 2931.29   16.85 2935.24   13.08 2938.76   11.71  2943.9   11.88
 2954.55   16.99 2980.19   24.99 2995.98   23.47 3709.11   25.52 3779.81   25.16
 3803.27   26.83 3824.87   23.45 3846.46   26.14 4156.33   24.97 4224.42   25.98
 4259.56   24.85 4310.67   26.68 4352.59   25.28 4823.43   26.67  5680.8    32.2
#Mann= 5 ,-1 , 0
       0     .12       0 2902.84     .06       0 2980.19     .12       0
 3709.11     .99       0 3803.27     .12       0
#Block Obstruct= 3 ,-1
 3803.27    5200   26.83    2300    2900    23.6    2985    3002    23.6
Bank Sta=2902.84,2980.19
XS Rating Curve= 0
Exp/Cntr=.3,.1

Type RM Length L Ch R = 1 ,11199.42,1024.4,1040.12,1058.85
BEGIN DESCRIPTION:
434v7
Bank Station offset =      2430
Based on visual inspection of cross sections and water surface elevations at this section and the next d/s sections, there is 0.2 % chance flow in both lob and rob.
END DESCRIPTION:
XS GIS Cut Line= 4
     3256019.548    13857345.912     3254139.423    13855694.802
     3254059.166    13855577.603     3251987.465    13853654.911
#Sta/Elev= 30
       0   25.82  641.63   25.57  852.58   24.75 1999.13   23.48 2195.41   22.48
 2368.29   23.84  2491.7    22.4    2510   22.65 2526.98   24.51 2547.11   18.97
 2560.28   13.76 2564.75   13.01 2570.46    10.1 2575.87   11.03 2578.47   14.37
 2593.39   16.76 2613.33   22.89  2633.1   21.45 2642.11    22.4 2642.27   21.75
 3031.15    24.3 3701.87   24.76 3727.42   26.67 3750.35   25.04 4159.26   26.33
 4191.95   27.61 4255.37   26.34 4341.08   27.96 4807.76   29.73 5470.68   30.56
#Mann= 3 , 0 , 0
       0     .12       0 2526.98     .04       0 2613.33      .1       0
#Block Obstruct= 1 ,-1
    2616 2642.11    22.4
Bank Sta=2526.98,2613.33
XS Rating Curve= 0
Exp/Cntr=.3,.1

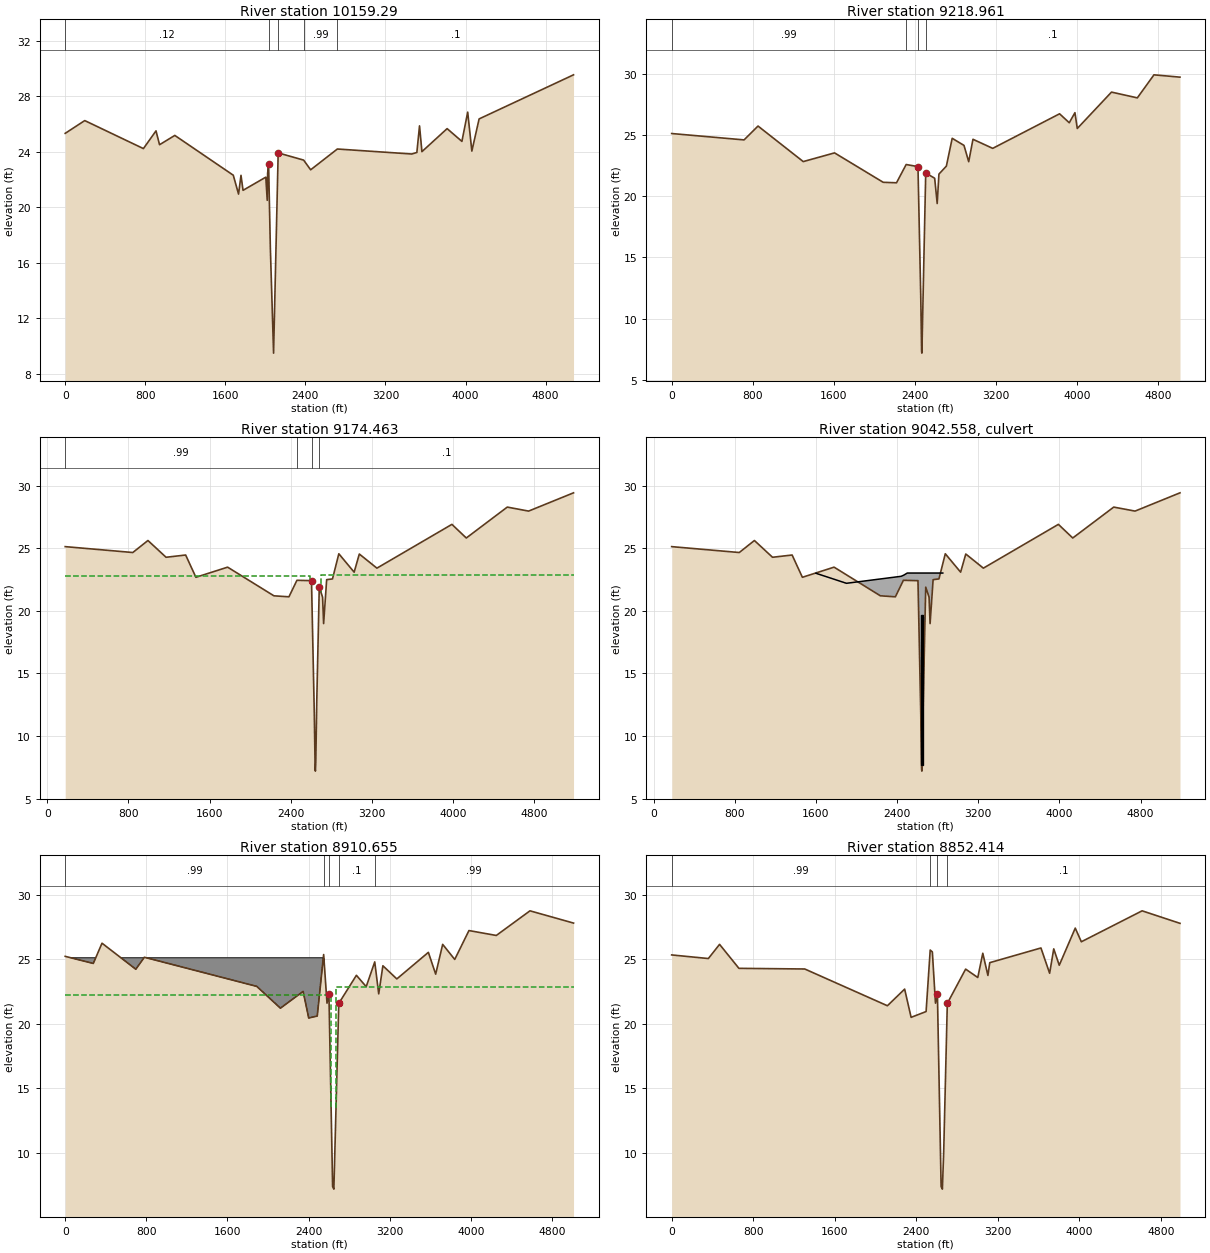
Type RM Length L Ch R = 1 ,10159.29,956.62,940.34,920.62
BEGIN DESCRIPTION:
434v8
Bank Station offset =      2918
the low area on the left overbank is a cleared area in the overbank and appears to re-enter channel, therefore is effective flow area (mbb)
END DESCRIPTION:
XS GIS Cut Line= 4
     3256301.721    13856609.186     3254991.237    13855073.589
     3254896.417    13854987.337     3252742.719    13852997.109
#Sta/Elev= 30
       0   25.33  195.22   26.25  781.48   24.23  907.37   25.51  942.65   24.51
 1095.41   25.18  1679.6   22.31 1732.14   20.95 1756.54    22.3    1777   21.22
 2004.52   22.17 2018.77    20.5 2022.77   22.45 2032.25   23.11 2049.88   17.08
 2082.12    9.48  2128.1   23.92 2382.48    23.4 2452.72    22.7  2719.5    24.2
    3463   23.84 3513.89   23.95 3540.49   25.87 3564.49   24.01 3816.35   25.67
 3964.03   24.75 4021.93   26.86 4063.42   24.05 4135.88   26.37 5079.43   29.55
#Mann= 5 ,-1 , 0
       0     .12       0 2032.25     .04       0  2128.1      .1       0
 2382.48     .99       0  2719.5      .1       0
Bank Sta=2032.25,2128.1
XS Rating Curve= 0
Exp/Cntr=.3,.1

Type RM Length L Ch R = 1 ,9218.961,36.46,44.5,49.81
BEGIN DESCRIPTION:
434s2u.  XS 4/4, Sjolander  Road and East Lynchburg Road.  This is a single structure that passes beneath 2 roads, hence the sections are designated s2u at u/s and s3d at d/s.  Use lowest low chord and highest high chord.
Assigned ineffective 0.99 on near lob as water will not enter stream.
Bank Station offset =      2530
END DESCRIPTION:
XS GIS Cut Line= 5
     3256419.656    13856503.501     3255518.936    13854292.813
      3255381.88    13854218.004     3255175.257    13853843.768
     3254221.315    13852032.292
#Sta/Elev= 30
       0   25.11  714.61   24.59  852.44   25.72 1298.86   22.82 1607.95   23.53
 2088.03   21.13 2219.52   21.09 2314.79   22.58  2431.4   22.41 2458.86   11.83
 2467.39    7.32 2469.92    7.19 2507.94   21.89 2596.35   21.46 2621.17    19.4
 2638.31    21.8 2711.77   22.45 2769.32   24.72 2885.79   24.14 2932.35   22.81
 2974.36   24.64 3169.31    23.9 3829.25   26.72 3924.88   25.99 3980.92   26.81
 4004.03   25.52  4341.9   28.49 4596.95   28.02 4761.14    29.9 5018.07   29.71
#Mann= 4 ,-1 , 0
       0     .99       0 2314.79     .12       0  2431.4     .04       0
 2507.94      .1       0
Bank Sta=2431.4,2507.94
XS Rating Curve= 0
Exp/Cntr=.5,.3

Type RM Length L Ch R = 1 ,9174.463,246.95,263.81,279.43
BEGIN DESCRIPTION:
Copy of 434s2u, Sjolander  Road and East Lynchburg Road.  XS 3/4.  Adjust elevations as needed.  This is a single structure that passes beneath 2 roads.
Assigned special ineffective 0.99 on near lob as water will not enter stream.  Based normal ineffective values on high ground adjacent to channel; it is judged that water beyond the high banks will not flow effectively.
Bank Station offset =      2533
END DESCRIPTION:
XS GIS Cut Line= 5
     3256443.798    13856472.184     3255533.425    13854262.686
     3255414.031    13854172.237     3255225.999    13853762.581
     3254326.247    13851952.612
#Sta/Elev= 30
     177   25.13  843.49   24.66  992.73   25.62 1171.33   24.28  1364.5   24.46
 1465.68   22.68 1778.05   23.49 2234.52    21.2 2382.71   21.12 2461.65   22.44
 2605.18   22.41 2632.64   11.83 2641.17    7.32  2643.7    7.19 2647.57    7.92
 2656.98   12.72 2681.72   21.89 2714.48   21.09 2724.65   18.98 2754.72   22.49
 2812.07   22.55 2874.66   24.56 3025.61   23.09 3076.64   24.54 3250.05   23.41
 3989.56   26.91 4131.21   25.82  4535.3   28.29 4745.63   27.97 5188.51   29.43
#Mann= 4 ,-1 , 0
     177     .99       0 2461.65     .12       0 2605.18     .04       0
 2681.72      .1       0
#XS Ineff= 2 , 0
       0    2591   22.76    2696       0   22.86
Permanent Ineff=
       F       F
Bank Sta=2605.18,2681.72
XS Rating Curve= 0
Exp/Cntr=.5,.3

Type RM Length L Ch R = 2 ,9042.558,,,
BEGIN DESCRIPTION:
434s3 and 434s2 - Sjolander  Road and East Lynchburg Road (a single set of double box culverts that passes beneath both roads)
 Used highest high chord for roadway data.
END DESCRIPTION:
Bridge Culvert--1,0,0,-1, 0
Deck Dist Width WeirC Skew NumUp NumDn MinLoCord MaxHiCord MaxSubmerge Is_Ogee
64,136,2.6,0, 7, 7, , , .95, 0, 0,0,,
    1600    1900  2439.6    2467 2499.63    2800    2850
      23    22.2   22.76   22.86   23.02   23.02   23.02
                                                        
    1600    2100 2610.87    2649 2673.62    2800    2850
      23    22.2   22.76   22.86   23.02   23.02   23.02
                                                        
BR Coef=-1 , 0 , 0 ,, 0 ,,,.8,-1,,0,
WSPro=,,,, 1 ,,,, 0 ,,,, 0 ,,,,-1 ,-1 ,-1 , 0 , 0 , 0 , 0 , 0
Multiple Barrel Culv=2,12,12,175.5,.013,.7,1,8,3,7.69,7.41, 2,Culvert #1  , 0 ,30
 2637.37 2637.65 2650.35 2650.35
Culvert Bottom n=.013
BC Design=,, 0 ,, 0 ,,,,,,

Type RM Length L Ch R = 1 ,8910.655,63.33,58.24,53.31
BEGIN DESCRIPTION:
Copy of 434s3d.  XS 2/4, Sjolander  Road and East Lynchburg Road.  Adjust elevations as needed.  This is a single structure that passes beneath 2 roads.  Ineffective area assigned at near LOB as flow is ineffective - cannot re-enter stream, based on review of data.
Bank Station offset =      2351
END DESCRIPTION:
XS GIS Cut Line= 5
     3256669.955    13856457.992     3255701.019    13854094.732
     3255594.888    13853943.495     3255444.188    13853574.837
     3254698.286    13851854.696
#Sta/Elev= 30
       0   25.23  276.99   24.68  362.89   26.25  696.32   24.23  780.47   25.16
 1888.96    22.9 2122.04   21.21 2345.85   22.51 2400.93   20.45 2485.18    20.6
 2548.29   25.37 2581.35    21.6 2600.34   22.32  2636.7    7.38 2648.95    7.18
 2697.43   21.58 2871.24   23.76 2967.86   22.88 3052.04    24.8  3091.3   22.32
 3132.31    24.5 3269.89   23.48 3580.84   25.54 3652.84   23.85 3721.84   26.16
 3840.72   24.99 3980.99   27.23 4250.66   26.85 4582.68   28.76 5012.11   27.81
#Mann= 5 ,-1 , 0
       0     .99       0 2548.29     .12       0 2600.34     .04       0
 2697.43      .1       0 3052.04     .99       0
#XS Ineff= 2 , 0
       0    2622    22.2    2670       0   22.86
Permanent Ineff=
       F       F
#Block Obstruct= 2 , 0
       0 2554.18   25.12               0
Bank Sta=2600.34,2697.43
XS Rating Curve= 0
Exp/Cntr=.5,.3

Type RM Length L Ch R = 1 ,8852.414,945.14,951.44,959.51
BEGIN DESCRIPTION:
434s3d.  XS 1/4, Sjolander  Road and East Lynchburg Road.  This is a single structure that passes beneath 2 roads.
Bank Station offset =      2344
END DESCRIPTION:
XS GIS Cut Line= 5
     3256738.099    13856416.368     3255742.792    13854040.974
     3255629.722    13853909.059     3255317.334    13853153.682
     3254789.621      13851834.4
#Sta/Elev= 30
       0   25.34  360.01   25.06  469.91   26.16   659.9    24.3 1305.64   24.25
  2116.8    21.4 2285.82   22.69 2349.35    20.5 2496.34   20.95 2536.71   25.72
 2557.74   25.57 2588.41    21.6  2607.4   22.32 2643.76    7.38 2656.01    7.18
 2668.97   10.04 2704.49   21.58 2884.25   24.24 3003.49   23.59 3052.56   25.47
 3102.89   23.75 3121.01   24.74 3623.29   25.88 3708.37   23.92 3748.76   25.81
  3802.8   24.54 3959.96   27.42 4019.51   26.36 4615.88   28.76 4987.56   27.79
#Mann= 4 ,-1 , 0
       0     .99       0 2536.71     .12       0  2607.4     .04       0
 2704.49      .1       0
Bank Sta=2607.4,2704.49
XS Rating Curve= 0
Exp/Cntr=.3,.1