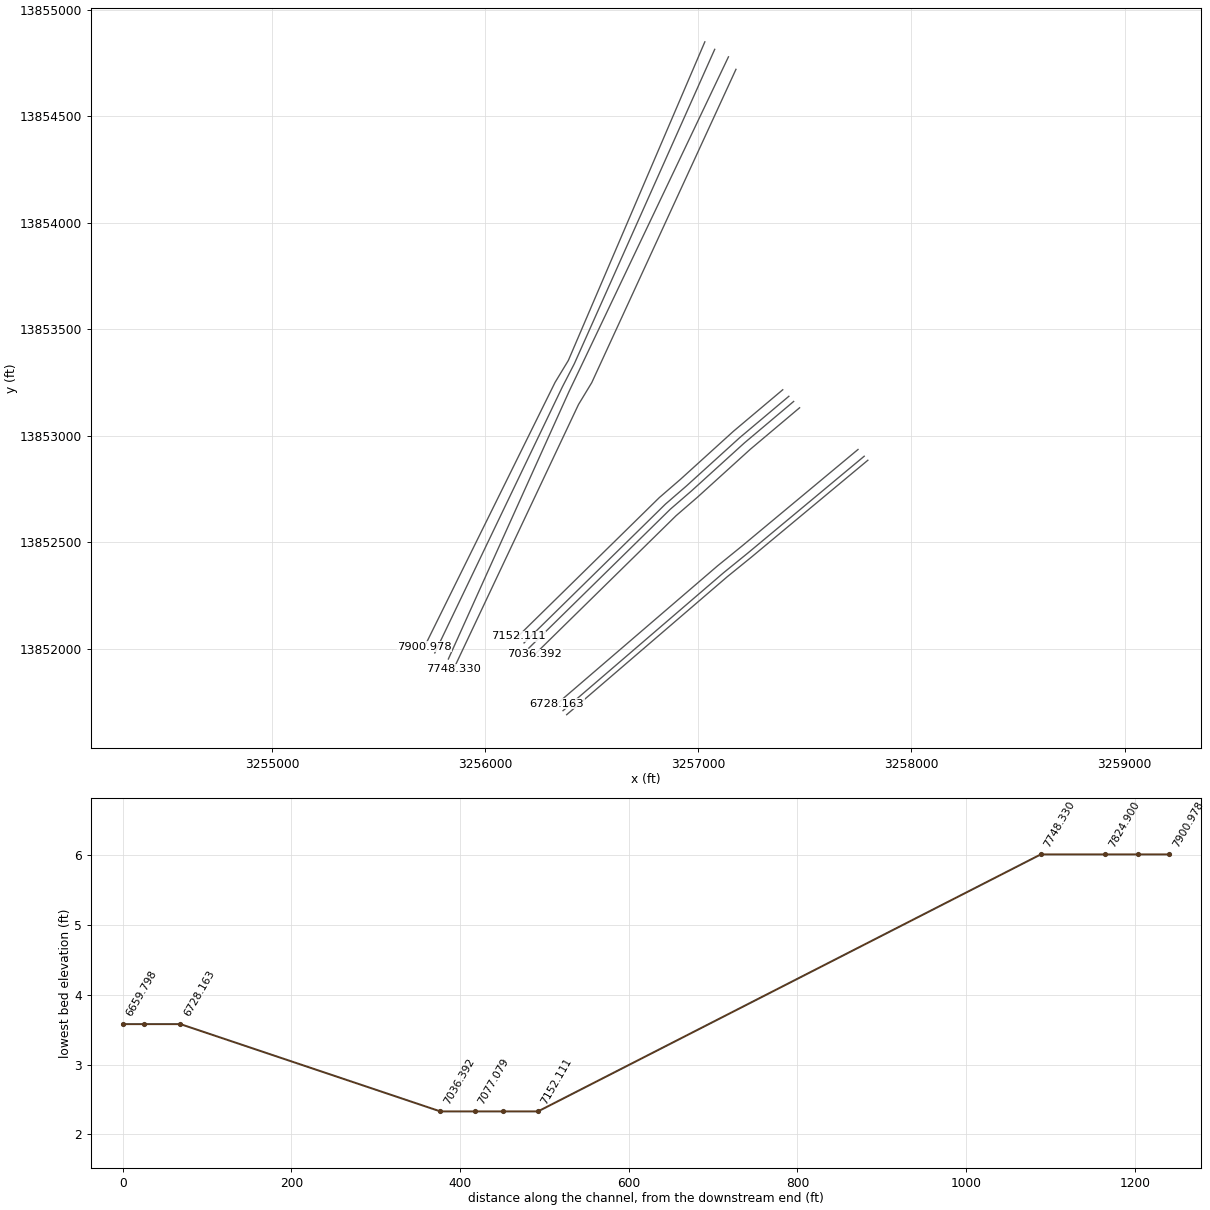
HEC-RAS study Q112-00-00.prj: Q112-00-00

--- Q112-00-00.g04 (geometry) --- (continued)

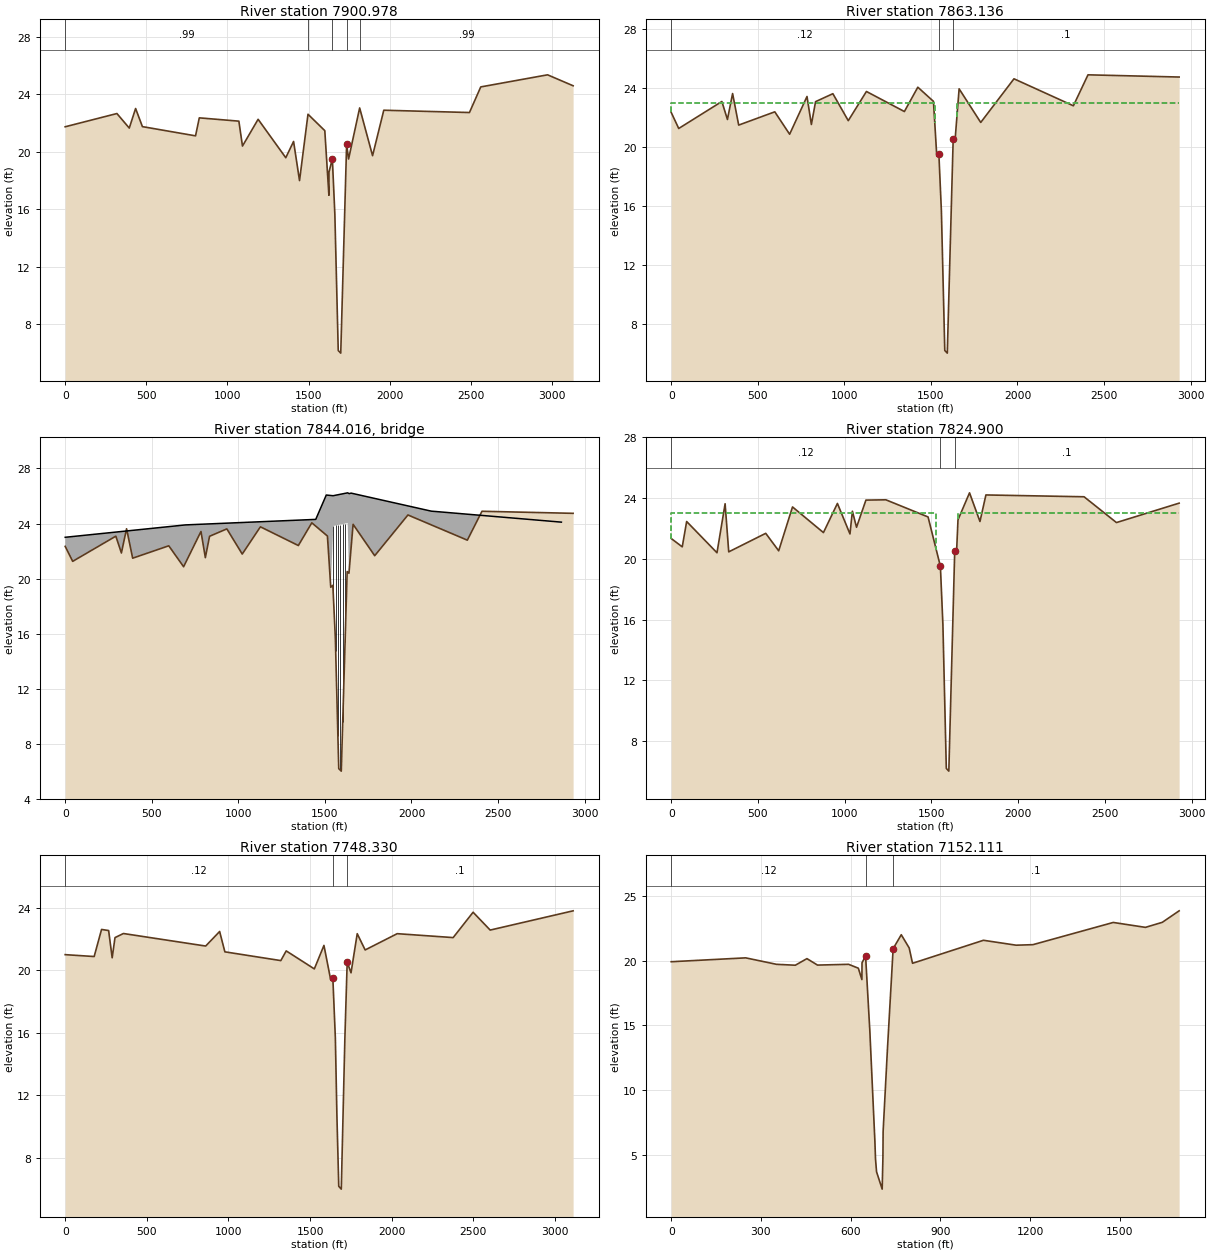
Type RM Length L Ch R = 1 ,7900.978,34.6,37.84,41.68
BEGIN DESCRIPTION:
434s4u, Dayton-Goose Creek RR.  XS 4/4.
Bank Station offset =      3302
END DESCRIPTION:
XS GIS Cut Line= 4
     3257030.614      13854848.7     3256390.114    13853353.751
     3256327.868     13853250.96      3255715.01    13852010.406
#Sta/Elev= 30
       0   21.74  318.79   22.66   394.9   21.65  433.95   23.01  475.99   21.75
  803.34   21.11  826.51   22.36 1070.38   22.13  1092.6    20.4 1188.97   22.26
 1359.44   19.59 1407.53   20.72 1444.18      18 1496.35   22.61 1599.96   21.47
 1625.22   16.98 1625.68   18.59  1646.5   19.51 1661.91   15.66 1682.76    6.19
 1698.21    6.01 1734.38   20.51 1746.55    19.5 1814.75   23.05 1894.33   19.73
 1963.47   22.89 2491.42   22.73 2561.08   24.51 2972.88   25.35 3130.23   24.59
#Mann= 5 ,-1 , 0
       0     .99       0 1496.35     .12       0  1646.5     .04       0
 1734.38      .1       0 1814.75     .99       0
Bank Sta=1646.5,1734.38
XS Rating Curve= 0
Exp/Cntr=.5,.3

Type RM Length L Ch R = 1 ,7863.136,36.65,38.24,40.38
BEGIN DESCRIPTION:
Copy of 434s4u, Dayton-Goose Creek RR.  XS 3/4.  Adjust elevations as needed.
Bank Station offset =      3303
END DESCRIPTION:
XS GIS Cut Line= 4
      3257076.92    13854813.529     3256418.314    13853338.567
     3256362.254    13853229.993     3255763.573    13851981.624
#Sta/Elev= 30
       0   22.34  43.348   21.25 292.555   23.08 324.748   21.86 354.555   23.62
 389.738   21.48 598.274   22.38 683.965   20.86 784.352   23.42 809.592   21.52
 833.827   23.07 933.716   23.611022.649   21.781127.575   23.761346.824    22.4
1424.433   24.051514.709   23.091533.945   19.37 1546.02   19.511560.501   15.66
1580.093    6.191594.611    6.01  1628.6   20.511639.049   20.391662.908   23.94
1787.784   21.661979.792   24.622322.807   22.79 2407.37   24.892933.739   24.74
#Mann= 3 ,-1 , 0
       0     .12       0 1546.02     .04       0  1628.6      .1       0
#XS Ineff= 2 , 0
       01522.302      23  1650.1       0      23
Permanent Ineff=
       F       F
Bank Sta=1546.02,1628.6
XS Rating Curve= 0
Skew Angle= 20
Exp/Cntr=.5,.3

Type RM Length L Ch R = 3 ,7844.016,,,
BEGIN DESCRIPTION:
434s4-Dayton-Goose Creek RR
Track exteded using elevations from tin.
END DESCRIPTION:
Bridge Culvert--1,0,-1,-1, 0
Deck Dist Width WeirC Skew NumUp NumDn MinLoCord MaxHiCord MaxSubmerge Is_Ogee
14,10,2.6,20, 10, 11, , , .95, 0, 0,0,,
       0 695.3731447.127    15081547.3641631.532 1640.291651.0962114.3082866.062
      23    23.9    24.3   26.07   26.02   26.23   26.17   26.21    24.9    24.1
       0       0       0       0   23.82   24.03       0       0       0       0
       0 695.3731447.1271513.6381553.002 1637.171645.9281656.7342114.3082866.062
2928.082
      23    23.9    24.3   26.07   26.02   26.23   26.17   26.21    24.9    24.1
    23.6
       0       0       0       0   23.82   24.03       0       0       0       0
        
Pier Skew, UpSta & Num, DnSta & Num=  ,1549.055, 2 ,1554.693, 2 , 0 , 0 , 0 ,0,
       1       1
       0   24.14
       1       1
       0   24.14
Pier Skew, UpSta & Num, DnSta & Num=  ,1562.408, 2 ,1568.046, 2 , 0 , 0 , 0 ,0,
       1       1
       0   24.24
       1       1
       0   24.24
Pier Skew, UpSta & Num, DnSta & Num=  ,1575.188, 2 ,1580.826, 2 , 0 , 0 , 0 ,0,
       1       1
       0   24.28
       1       1
       0   24.28
Pier Skew, UpSta & Num, DnSta & Num=  ,1589.255, 2 ,1594.893, 2 , 0 , 0 , 0 ,0,
       1       1
       0   24.16
       1       1
       0   24.16
Pier Skew, UpSta & Num, DnSta & Num=  ,1602.9, 2 ,1608.538, 2 , 0 , 0 , 0 ,0,
       1       1
       0   24.17
       1       1
       0   24.17
Pier Skew, UpSta & Num, DnSta & Num=  ,1616.525, 2 ,1622.163, 2 , 0 , 0 , 0 ,0,
       1       1
       0   24.22
       1       1
       0   24.22
BR Coef=-1 , 1 , 1 ,.9, 0 ,,,.8,-1,1.2,1,
WSPro=,,,, 1 ,,,, 0 ,,,, 0 ,,,,-1 ,-1 ,-1 , 0 , 0 , 0 , 0 , 0
BC Design=,, 0 ,, 0 ,,,,,,

Type RM Length L Ch R = 1 ,7824.900,81.08,76.57,71.34
BEGIN DESCRIPTION:
Copy of 434s4u, Dayton-Goose Creek RR.  XS 2/4.  Adjust elevations as needed.
Bank Station offset =      3297
END DESCRIPTION:
XS GIS Cut Line= 4
     3257141.415     13854778.35     3256446.812    13853319.758
     3256393.097    13853207.432      3255827.21    13851953.085
#Sta/Elev= 30
       0   21.34  63.627   20.79  89.017   22.46 263.884    20.4 310.719   23.63
  331.58   20.46   544.9   21.68 619.615   20.53 699.319   23.42 877.588   21.73
 958.176   23.651030.542   21.641044.487   23.141068.327   22.081122.547   23.87
1237.538   23.891480.777   22.761551.846   19.511566.327   15.661585.919    6.19
1600.438    6.011634.426   20.511644.875   20.391653.267   22.571719.797   24.35
1779.966   22.461814.246   24.212380.053   24.092566.902   22.392928.204   23.67
#Mann= 3 ,-1 , 0
       0     .12       01551.846     .04       01634.426      .1       0
#XS Ineff= 2 , 0
       0 1527.94      231655.738       0      23
Permanent Ineff=
       F       F
Bank Sta=1551.846,1634.426
XS Rating Curve= 0
Skew Angle= 20
Exp/Cntr=.5,.3

Type RM Length L Ch R = 1 ,7748.330,610.41,596.22,580.41
BEGIN DESCRIPTION:
Copy of 434s4u, Dayton-Goose Creek RR.  XS 1/4.  Adjust elevations as needed.
Bank Station offset =      3309
END DESCRIPTION:
XS GIS Cut Line= 4
     3257176.594    13854719.718     3256500.025     13853249.77
     3256437.779    13853146.978     3255851.521    13851905.403
#Sta/Elev= 30
       0   20.99   177.5   20.87  222.79    22.6  266.14   22.53  287.82   20.79
  305.18   22.08  356.81   22.34   860.6   21.54  946.14   22.47  978.15   21.17
  1320.9   20.61 1353.93   21.23 1526.19   20.08  1585.1   21.58  1626.7   19.37
 1639.55   19.51 1654.96   15.66 1664.59   10.65 1675.81    6.19 1691.26    6.01
 1713.16    15.6 1727.43   20.51 1750.95   19.83 1788.94   22.33 1837.45   21.29
 2033.87   22.33 2376.59   22.08 2498.68    23.7 2603.32   22.56 3111.37   23.79
#Mann= 3 , 0 , 0
       0     .12       0 1639.55     .04       0 1727.43      .1       0
Bank Sta=1639.55,1727.43
XS Rating Curve= 0
Exp/Cntr=.3,.1

Type RM Length L Ch R = 1 ,7152.111,42.01,41.96,41.94
BEGIN DESCRIPTION:
434s5u, Foot Bridge.  XS 4/4.
Bank Station offset =      4294
END DESCRIPTION:
XS GIS Cut Line= 5
     3257396.059    13853216.377      3257164.61    13853021.472
     3256916.348    13852796.302     3256816.931    13852710.336
     3256153.544    13852059.132
#Sta/Elev= 30
       0   19.93  249.14   20.23     352   19.73  415.13   19.66   453.9   20.17
   489.3   19.67  593.26   19.73  625.81   19.43  637.75   18.55  638.17   19.85
  650.07   20.38  664.26   14.59  681.21    6.03   683.3    4.65  686.79    3.67
  705.58    2.33  708.05    4.76  708.72    6.78  722.92   13.06  742.22   20.94
  769.41   22.02  795.87      21  807.09   19.81 1044.35   21.59 1153.71   21.21
 1209.64   21.25 1478.42   22.97 1586.04   22.59 1642.43   22.98 1698.77   23.87
#Mann= 3 ,-1 , 0
       0     .12       0  650.07     .04       0  742.22      .1       0
Bank Sta=650.07,742.22
XS Rating Curve= 0
Exp/Cntr=.5,.3

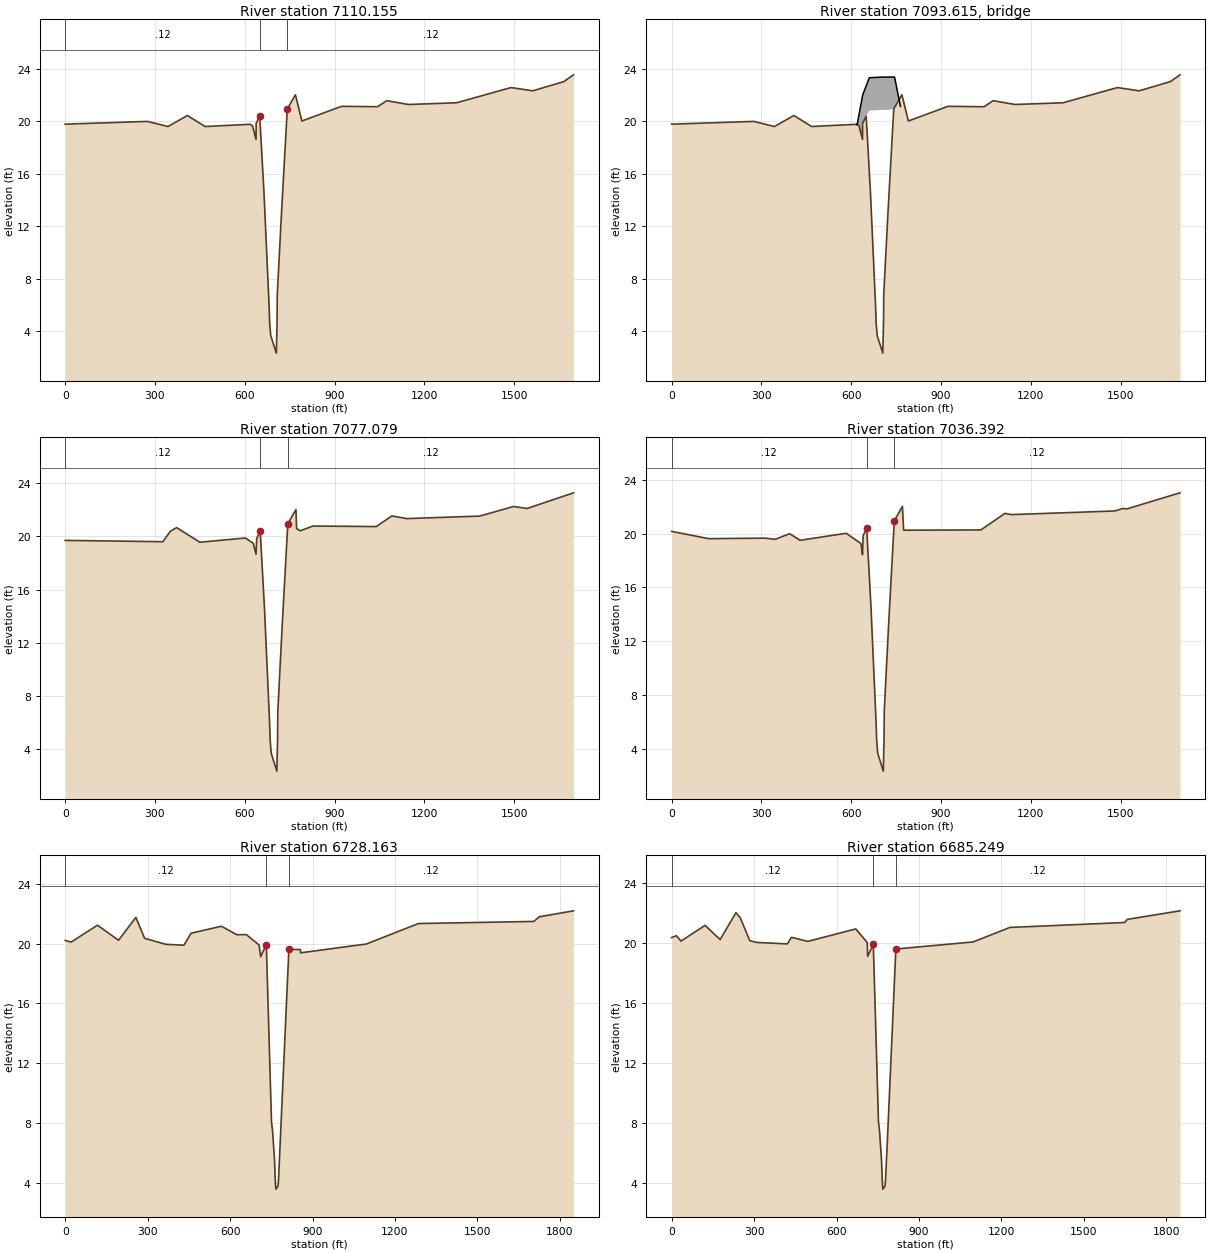
Type RM Length L Ch R = 1 ,7110.155,33.12,33.08,33.06
BEGIN DESCRIPTION:
Copy of 434s5u, Foot Bridge.  XS 3/4.  Adjust elevations as needed.
Bank Station offset =      4294
END DESCRIPTION:
XS GIS Cut Line= 5
     3257424.827    13853185.811     3257193.378    13852990.907
     3256945.116    13852765.737     3256845.699    13852679.771
     3256182.312    13852028.567
#Sta/Elev= 30
       0   19.78  274.49   19.99  343.55    19.6   408.4   20.44  467.63    19.6
  618.21   19.77  626.13   19.65  637.75   18.62  638.17   19.85  650.07   20.38
  664.26   14.59  681.21    6.03   683.3    4.65  686.79    3.67  705.58    2.33
  708.05    4.76  708.72    6.78  722.92   13.06  742.22   20.94  769.41   22.02
  790.99   20.02  923.42   21.14 1044.26   21.11 1074.24   21.57 1147.19   21.28
 1308.05   21.41  1489.7   22.57 1562.44   22.32  1666.2   23.02 1698.77   23.54
#Mann= 3 ,-1 , 0
       0     .12       0  650.07     .04       0  742.22     .12       0
Bank Sta=650.07,742.22
XS Rating Curve= 0
Exp/Cntr=.5,.3

Type RM Length L Ch R = 3 ,7093.615,,,
BEGIN DESCRIPTION:
434s5 - Foot Bridge
The WSEL not high enough to be ineffective. Hence ineffective stations removed.
END DESCRIPTION:
Bridge Culvert--1,0,-1,-1, 0
Deck Dist Width WeirC Skew NumUp NumDn MinLoCord MaxHiCord MaxSubmerge Is_Ogee
15,4,2.6,0, 7, 7, , , .95, 0, 0,0,,
     618     620  638.27  660.45  704.97  744.97  764.61
   19.75   19.75      22   23.32   23.37   23.37   21.13
       0       0       0   20.82   20.87   20.87       0
     600     620  639.27  661.45  705.97  744.39  765.61
   19.75   19.75      22   23.32   23.37   23.37   21.13
       0       0       0   20.82   20.87   20.87       0
BR Coef=-1 , 0 , 0 ,, 0 ,,,.8,-1,,1,
WSPro=,,,, 1 ,,,, 0 ,,,, 0 ,,,,-1 ,-1 ,-1 , 0 , 0 , 0 , 0 , 0
BC Design=,, 0 ,, 0 ,,,,,,

Type RM Length L Ch R = 1 ,7077.079,40.74,40.69,40.67
BEGIN DESCRIPTION:
Copy of 434s5u, Foot Bridge.  XS 2/4.  Adjust elevations as needed.
Bank Station offset =      4293
END DESCRIPTION:
XS GIS Cut Line= 5
     3257447.301    13853161.539     3257215.852    13852966.635
      3256967.59    13852741.465     3256868.173    13852655.498
     3256204.786    13852004.295
#Sta/Elev= 30
       0    19.7  326.47    19.6  351.05   20.38  372.27   20.66  450.28   19.56
  602.43   19.88  628.52   19.48  637.75   18.66  639.87   19.85  651.77   20.38
  665.96   14.59  682.91    6.03     685    4.65  688.49    3.67  707.28    2.33
  709.75    4.76  710.42    6.78  724.62   13.06  743.92   20.94  771.11   22.02
  773.28   20.59  784.99   20.42  827.87   20.78 1039.32   20.74 1091.77   21.54
 1141.78   21.34 1385.31   21.53 1498.32   22.25 1543.57    22.1 1698.77   23.28
#Mann= 3 ,-1 , 0
       0     .12       0  651.77     .04       0  743.92     .12       0
Bank Sta=651.77,743.92
XS Rating Curve= 0
Exp/Cntr=.5,.3

Type RM Length L Ch R = 1 ,7036.392,309.35,308.23,306.33
BEGIN DESCRIPTION:
Copy of 434s5u, Foot Bridge.  XS 1/4.  Adjust elevations as needed.
Bank Station offset =      4293
END DESCRIPTION:
XS GIS Cut Line= 5
     3257475.169    13853131.873     3257243.721    13852936.968
     3256995.458    13852711.798     3256896.041    13852625.832
     3256232.654    13851974.628
#Sta/Elev= 30
       0   20.16  123.91   19.62  312.45   19.66  345.55   19.57  394.26   19.99
  429.23    19.5   583.3   20.02  631.76   19.27  633.71    19.1  637.75   18.44
  639.87   19.85  651.77   20.38  665.96   14.59  682.91    6.03     685    4.65
  688.49    3.67  707.28    2.33  709.75    4.76  710.42    6.78  724.62   13.06
  743.92   20.94  771.11   22.02  775.22   20.25 1033.52   20.27 1113.63    21.5
 1135.42   21.41  1480.7   21.68 1509.23   21.87 1520.65   21.83 1698.77   23.03
#Mann= 3 , 0 , 0
       0     .12       0  651.77     .04       0  743.92     .12       0
Bank Sta=651.77,743.92
XS Rating Curve= 0
Exp/Cntr=.3,.1

Type RM Length L Ch R = 1 ,6728.163,42.9,42.92,42.88
BEGIN DESCRIPTION:
434s6u, Foot Bridge.  XS 4/4
Bank Station offset =      4233
END DESCRIPTION:
XS GIS Cut Line= 4
     3257749.323    13852936.202     3257202.046    13852480.834
       3257089.9    13852389.876     3256336.267    13851742.413
#Sta/Elev= 30
       0   20.22   21.87   20.11  117.47   21.24  193.98   20.23  257.15   21.76
  288.96   20.36  365.85   19.96  432.09    19.9  458.03    20.7  568.37   21.17
  624.68    20.6  659.11   20.61  705.72   19.91  711.21   19.13  731.94   19.94
  750.71    8.09  754.76    7.44  761.98    5.45  764.68    4.08  766.61    3.58
  774.65    3.79  776.36    4.21  814.01   19.62  856.26   19.61  856.35   19.39
 1096.15   19.98 1285.36   21.35  1705.5   21.49 1724.97    21.8 1849.91    22.2
#Mann= 3 ,-1 , 0
       0     .12       0  731.94     .04       0  814.01     .12       0
Bank Sta=731.94,814.01
XS Rating Curve= 0
Exp/Cntr=.5,.3

Type RM Length L Ch R = 1 ,6685.249,25.45,25.45,25.43
BEGIN DESCRIPTION:
Copy of 434s6u, Foot Bridge.  XS 3/4.  Adjust elevations as needed.
Bank Station offset =      4232
END DESCRIPTION:
XS GIS Cut Line= 4
     3257778.328    13852904.538     3257231.051     13852449.17
     3257118.904    13852358.212     3256365.272    13851710.749
#Sta/Elev= 30
       0   20.38   16.58   20.51   34.15   20.15  121.59    21.2  176.35   20.25
  234.09   22.05  249.72    21.7  284.17   20.18  308.16   20.06  421.39   19.96
  435.63    20.4  495.46   20.13  669.83   20.96  711.95   20.05  713.06   19.13
  733.79   19.94  752.56    8.09  756.61    7.44  763.83    5.45  766.53    4.08
  768.46    3.58   776.5    3.79  778.21    4.21  784.83    6.74  815.86   19.62
  1096.8   20.09 1230.79   21.06 1648.71   21.39  1658.4    21.6 1849.91   22.17
#Mann= 3 ,-1 , 0
       0     .12       0  733.79     .04       0  815.86     .12       0
Bank Sta=733.79,815.86
XS Rating Curve= 0
Exp/Cntr=.5,.3

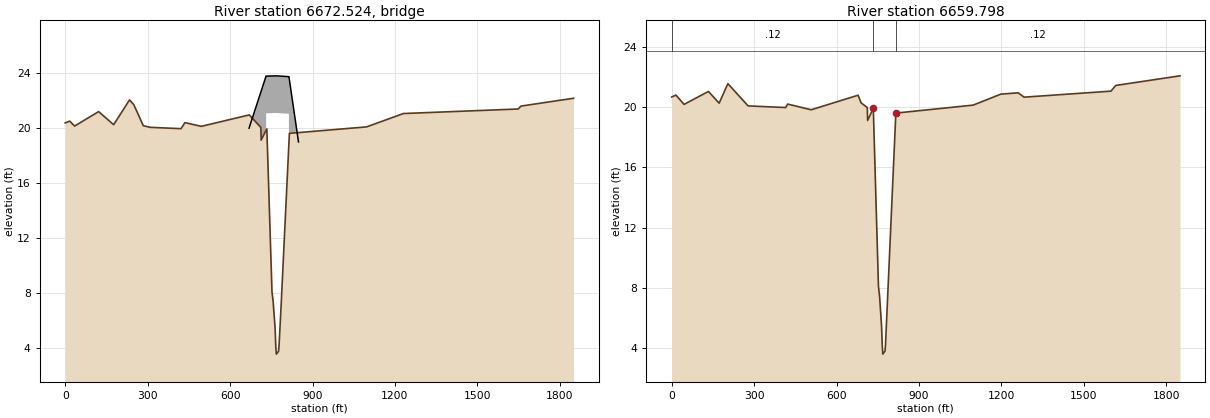
Type RM Length L Ch R = 3 ,6672.524,,,
BEGIN DESCRIPTION:
434s6- Foot Bridge
The WSEL not high enough to be ineffective. Hence ineffective stations removed.
END DESCRIPTION:
Bridge Culvert--1,0,-1,-1, 0
Deck Dist Width WeirC Skew NumUp NumDn MinLoCord MaxHiCord MaxSubmerge Is_Ogee
11,4,2.6,0, 7, 7, , , .95, 0, 0,0,,
     669     731  731.23   768.3  814.09   814.2     849
      20   23.78   23.78    23.8   23.74   23.74      19
       0       0   21.08    21.1   21.04       0       0
     669     731  731.23   768.3  814.09   814.2     849
      20   23.78   23.78    23.8   23.74   23.74      19
       0       0   21.08    21.1   21.04       0       0
BR Coef=-1 , 0 , 0 ,, 0 ,,,.8,-1,,1,
WSPro=,,,, 1 ,,,, 0 ,,,, 0 ,,,,-1 ,-1 ,-1 , 0 , 0 , 0 , 0 , 0
BC Design=,, 0 ,, 0 ,,,,,,

Type RM Length L Ch R = 1 ,6659.798,48.12,48.13,48.18
BEGIN DESCRIPTION:
Copy of 434s6u, Foot Bridge.  XS 2/4.  Adjust elevations as needed.
Bank Station offset =      4232
END DESCRIPTION:
XS GIS Cut Line= 4
     3257795.421    13852885.672     3257248.144    13852430.304
     3257135.997    13852339.346     3256382.365    13851691.883
#Sta/Elev= 30
       0   20.69   15.32   20.82   45.15    20.2  133.89   21.06   172.8   20.28
  204.59   21.58  278.06    20.1  414.91   19.99   422.2   20.22  507.76   19.84
  678.46   20.81  689.46    20.3  711.95   19.99  713.06   19.13  733.79   19.94
  752.56    8.09  756.61    7.44  763.83    5.45  766.53    4.08  768.46    3.58
   776.5    3.79  778.21    4.21  815.86   19.62 1097.04   20.15  1197.8   20.88
 1261.15   20.97 1282.41   20.68 1598.63   21.08 1616.14   21.46 1849.91    22.1
#Mann= 3 ,-1 , 0
       0     .12       0  733.79     .04       0  815.86     .12       0
Bank Sta=733.79,815.86
XS Rating Curve= 0
Exp/Cntr=.5,.3