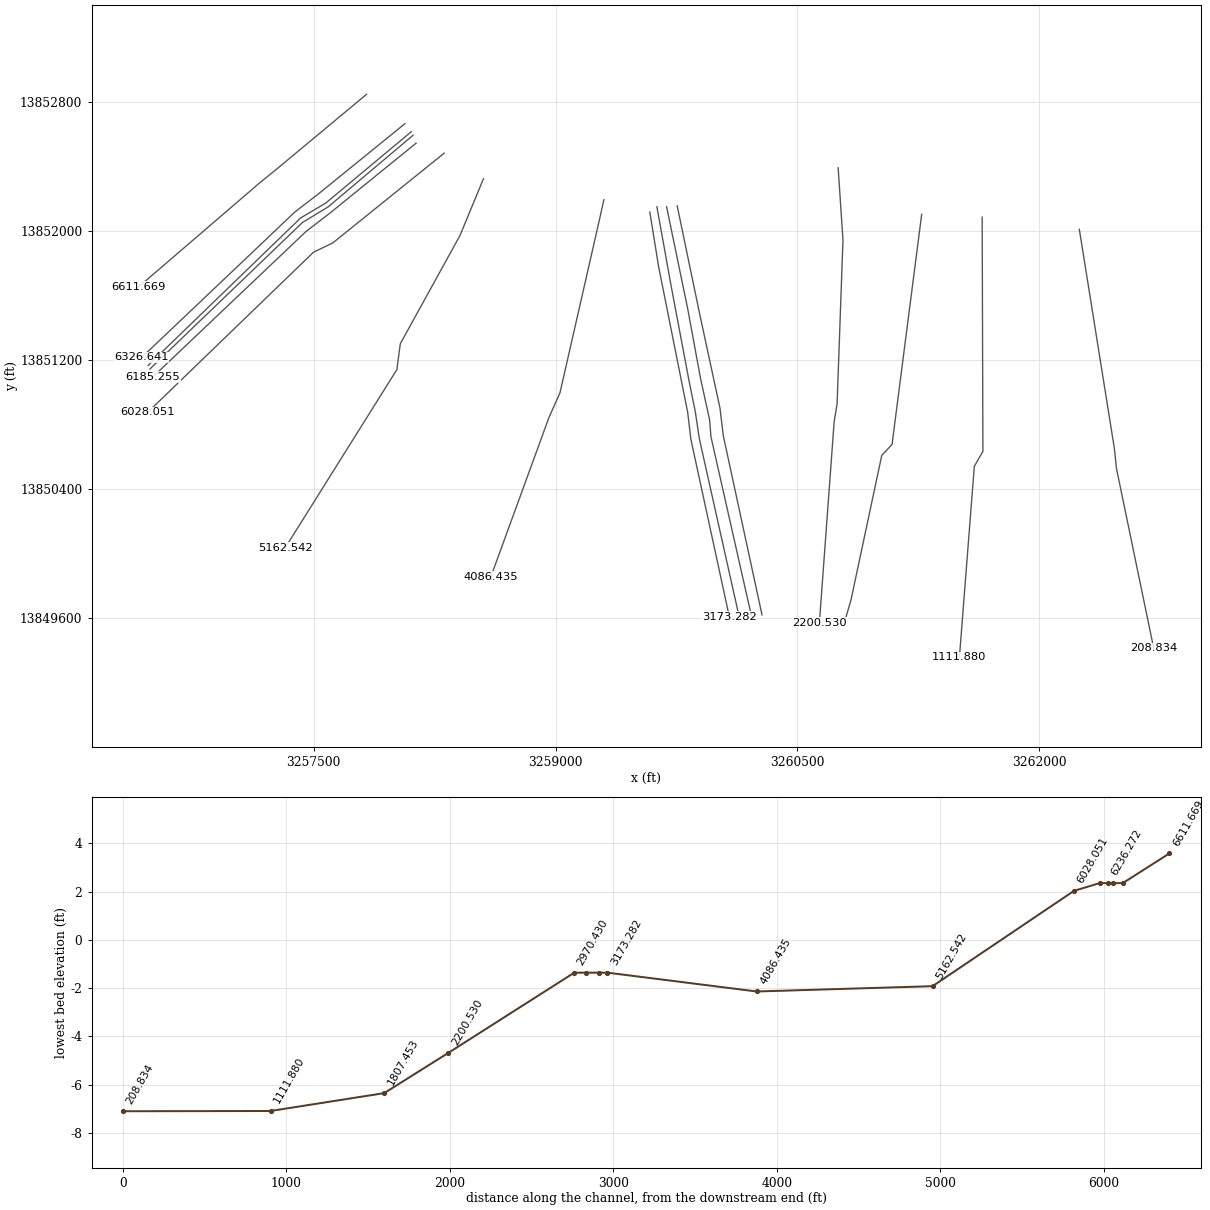
HEC-RAS study Q112-00-00.prj: Q112-00-00

--- Q112-00-00.g04 (geometry) --- (continued)

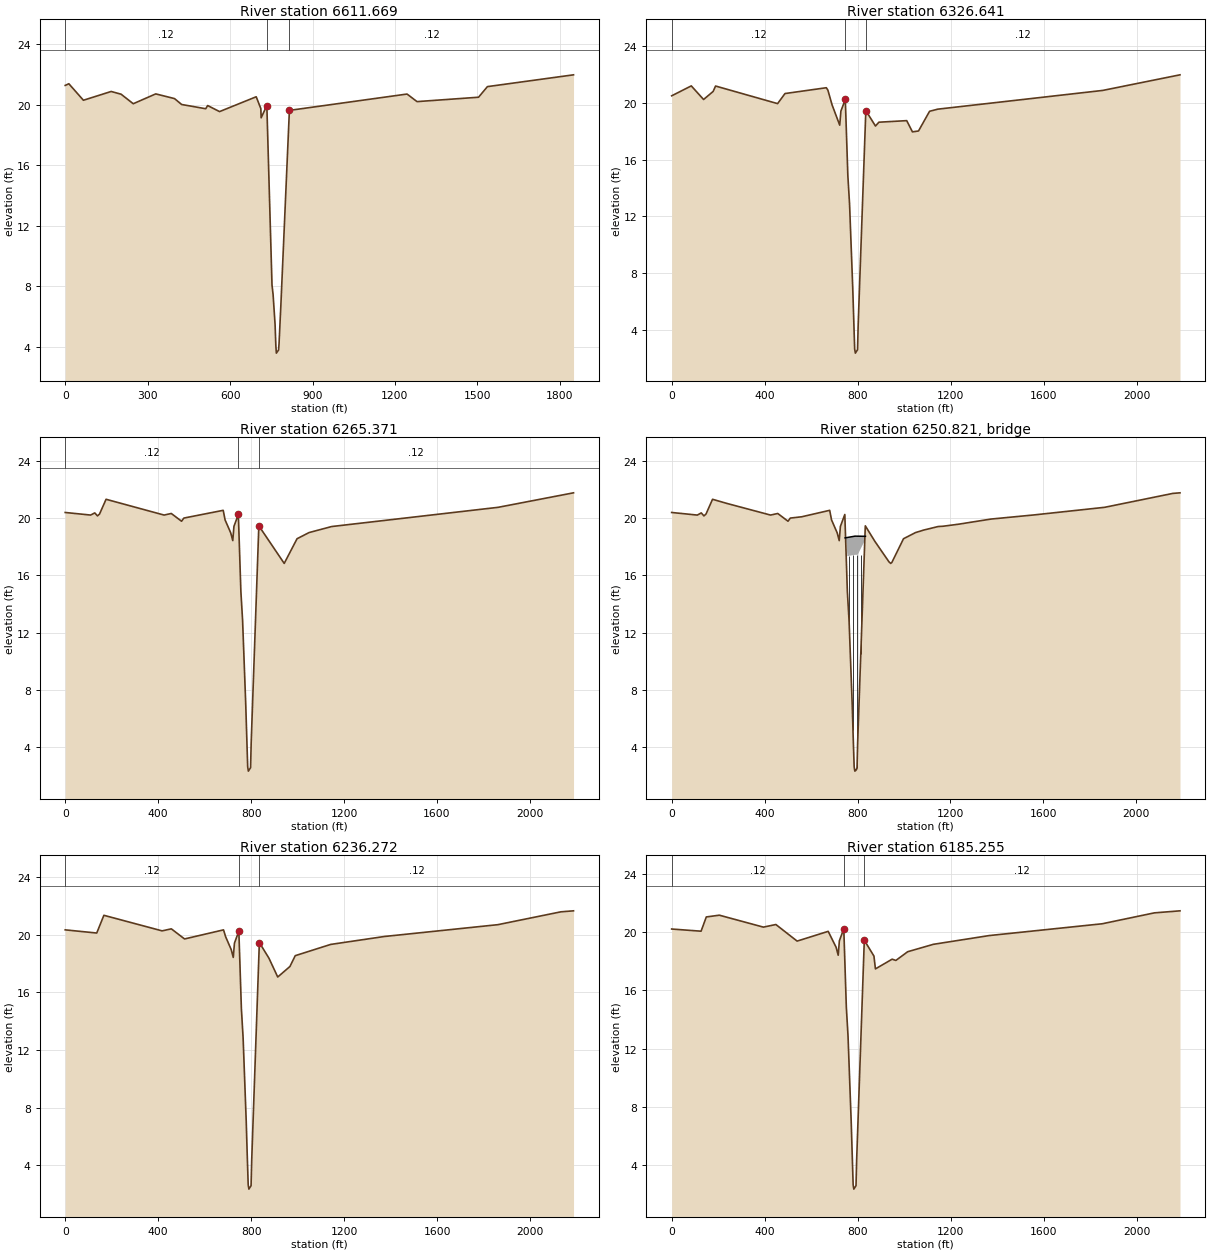
Type RM Length L Ch R = 1 ,6611.669,284.66,285.03,283.53
BEGIN DESCRIPTION:
Copy of 434s6u, Foot Bridge.  XS 1/4.  Adjust elevations as needed.
Bank Station offset =      4232
END DESCRIPTION:
XS GIS Cut Line= 4
      3257827.98    13852850.203     3257280.703    13852394.836
     3257168.556    13852303.878     3256414.924    13851656.415
#Sta/Elev= 30
       0   21.27   13.25   21.38   66.27   20.29  167.23   20.87  203.38   20.69
  247.61   20.06  329.49   20.71  397.75    20.4  423.72   20.01  511.29   19.73
  518.52   19.94  561.65   19.54  695.11   20.52  711.95   19.74  713.06   19.13
  733.79   19.94  752.56    8.09  756.61    7.44  763.83    5.45  766.53    4.08
  768.46    3.58   776.5    3.79  778.21    4.21  784.83    6.74  815.86   19.62
 1244.01    20.7 1280.35    20.2 1504.25   20.49 1536.54   21.19 1849.91   21.97
#Mann= 3 ,-1 , 0
       0     .12       0  733.79     .04       0  815.86     .12       0
Bank Sta=733.79,815.86
XS Rating Curve= 0
Exp/Cntr=.3,.1

Type RM Length L Ch R = 1 ,6326.641,65.1,61.27,54.28
BEGIN DESCRIPTION:
434s7u, Foot Bridge.  XS 4/4.
Bank Station offset =      4210
END DESCRIPTION:
XS GIS Cut Line= 4
     3258066.043    13852668.208     3257530.816    13852233.774
     3257383.009    13852120.077     3256433.719    13851218.607
#Sta/Elev= 30
       0   20.49    84.3   21.19  137.21   20.23  178.28    20.8  188.73   21.18
  455.28   19.94  487.12   20.65   664.7   21.06  671.46   20.89  689.32   19.86
  722.35   18.42  727.38   19.41  746.33   20.24  757.27   14.87  764.64   12.85
  778.13    7.02  786.59    2.64  789.56    2.35  798.91    2.59  801.59    4.32
  834.54   19.45  876.02   18.36  890.73   18.63 1010.28   18.74 1034.87   17.95
 1060.94   18.01 1108.56    19.4 1144.06   19.55 1852.78   20.87 2184.95   21.97
#Mann= 3 ,-1 , 0
       0     .12       0  746.33     .04       0  834.54     .12       0
Bank Sta=746.33,834.54
XS Rating Curve= 0
Exp/Cntr=.5,.3

Type RM Length L Ch R = 1 ,6265.371,28.89,29.1,30.13
BEGIN DESCRIPTION:
Copy of 434s7u, Foot Bridge.  XS 3/4.  Adjust elevations as needed.
Removed ineffective flow settings as station and elevation place them inside ground points.
Bank Station offset =      4212
END DESCRIPTION:
XS GIS Cut Line= 4
     3258105.513    13852618.267     3257575.662    13852176.378
     3257419.546    13852083.624     3256473.189    13851168.666
#Sta/Elev= 30
       0   20.38  109.39    20.2  127.35   20.35   138.9   20.14  147.74   20.27
  175.89    21.3  425.52    20.2  456.53   20.31  500.77   19.77  510.71   19.99
  680.05   20.53  688.18   19.86  712.39   18.96  721.21   18.42  726.24   19.41
  745.19   20.24  756.13   14.87   763.5   12.85  776.99    7.02  785.45    2.64
  788.42    2.35  797.77    2.59  800.45    4.32   833.4   19.45  942.64   16.83
  997.87   18.55 1049.65   18.98 1146.79    19.4 1863.59   20.74 2187.86   21.75
#Mann= 3 ,-1 , 0
       0     .12       0  745.19     .04       0   833.4     .12       0
Bank Sta=745.19,833.4
XS Rating Curve= 0
Exp/Cntr=.5,.3

Type RM Length L Ch R = 3 ,6250.821,,,
BEGIN DESCRIPTION:
434s7-Foot Bridge
The WSEL not high enough to be ineffective. Hence ineffective stations removed.
Based on observations, the ground data does not cross the roadway surface more than twice in the model for this structure.
END DESCRIPTION:
Bridge Culvert--1,0,-1,-1, 0
Deck Dist Width WeirC Skew NumUp NumDn MinLoCord MaxHiCord MaxSubmerge Is_Ogee
10,10,2.6,0, 4, 4, , , .95, 0, 0,0,,
  746.57  789.04  831.15     834
   18.61   18.73   18.72   18.72
   17.31   17.43   17.42   17.42
  748.57  791.04  833.15     834
   18.61   18.73   18.72   18.72
   17.31   17.43   17.42   17.42
Pier Skew, UpSta & Num, DnSta & Num=  ,763.74, 2 ,765.74, 2 , 0 , 0 , 0 ,0,
       1       1
       0   17.43
       1       1
       0   17.43
Pier Skew, UpSta & Num, DnSta & Num=  ,780.36, 2 ,782.36, 2 , 0 , 0 , 0 ,0,
       1       1
       0   17.43
       1       1
       0   17.43
Pier Skew, UpSta & Num, DnSta & Num=  ,797.08, 2 ,799.08, 2 , 0 , 0 , 0 ,0,
       1       1
       0   17.43
       1       1
       0   17.43
Pier Skew, UpSta & Num, DnSta & Num=  ,813.96, 2 ,815.96, 2 , 0 , 0 , 0 ,0,
       1       1
       0   17.43
       1       1
       0   17.43
BR Coef=-1 , 1 , 1 ,.9, 0 ,,,.8,-1,1.2,1,
WSPro=,,,, 1 ,,,, 0 ,,,, 0 ,,,,-1 ,-1 ,-1 , 0 , 0 , 0 , 0 , 0
BR U #Sta/Elev= 46
       0   20.38  109.39    20.2   110.6    20.2  127.35   20.35   138.9   20.14
  147.74   20.27  175.89    21.3   237.9   21.01  425.52    20.2  456.53   20.31
  500.77   19.77  510.71   19.99  559.66   20.08  680.05   20.53  688.18   19.86
  712.39   18.96  721.21   18.42  726.24   19.41  745.19   20.24  756.13   14.87
   763.5   12.85  776.99    7.02  781.07    4.82  785.45    2.64  788.42    2.35
  791.85    2.39  795.39    2.46  797.77    2.59  800.45    4.32   833.4   19.45
  874.88   18.36  935.25   16.94  942.64   16.83  947.81    16.9  997.87   18.55
 1049.65   18.98 1072.05   19.09 1083.72   19.15 1146.79    19.4  1167.6   19.42
 1233.88   19.56  1373.8   19.92 1559.91   20.21 1863.59   20.74 2157.14   21.71
 2187.86   21.75
BR U #Mann= 3
       0     .12  745.19     .04   833.4     .12
BC Design=,, 0 ,, 0 ,,,,,,

Type RM Length L Ch R = 1 ,6236.272,46.14,51.02,59.13
BEGIN DESCRIPTION:
Copy of 434s7u, Foot Bridge.  XS 2/4.  Adjust elevations as needed.  Removed ineffective flow settings as station and elevation place them inside ground points.
Bank Station offset =      4210
END DESCRIPTION:
XS GIS Cut Line= 4
      3258116.79    13852596.518     3257589.022    13852151.567
     3257430.997     13852055.76     3256484.466    13851146.918
#Sta/Elev= 30
       0   20.33  135.68   20.11  166.44   21.34  416.91   20.26  456.65    20.4
  513.58    19.7  681.28   20.33  690.17   19.86  714.38   18.96   723.2   18.42
  728.23   19.41  747.18   20.24  758.12   14.87  765.49   12.85  778.98    7.02
  783.06    4.82  787.44    2.64  790.41    2.35  799.76    2.59  802.44    4.32
  835.39   19.45  876.87   18.36  914.47   17.06  967.01   17.79  989.85   18.54
 1142.31   19.32 1373.45   19.87 1861.83   20.69 2132.81   21.58 2187.32   21.65
#Mann= 3 ,-1 , 0
       0     .12       0  747.18     .04       0  835.39     .12       0
Bank Sta=747.18,835.39
XS Rating Curve= 0
Exp/Cntr=.5,.3

Type RM Length L Ch R = 1 ,6185.255,163.01,157.2,144.99
BEGIN DESCRIPTION:
Copy of 434s7u, Foot Bridge.  XS 1/4.  Adjust elevations as needed.
Bank Station offset =      4217
END DESCRIPTION:
XS GIS Cut Line= 4
     3258135.316    13852547.383     3257600.089    13852112.949
     3257452.283    13851999.251     3256502.993    13851097.782
#Sta/Elev= 30
       0   20.22   126.4   20.07  148.89   21.05  204.92   21.17  394.31   20.35
  447.84   20.53   539.2   19.39  672.81   20.06  706.98   18.96   715.8   18.42
  720.83   19.41  739.78   20.24  750.72   14.87  758.09   12.85  771.58    7.02
  780.04    2.64  783.01    2.35  792.36    2.59  795.04    4.32  827.99   19.45
  869.47   18.36  875.83   17.48  947.78   18.15  963.55   18.06 1014.43   18.66
 1125.19   19.17 1364.67   19.77  1850.4   20.58 2074.84   21.33 2184.95   21.47
#Mann= 3 ,-1 , 0
       0     .12       0  739.78     .04       0  827.99     .12       0
Bank Sta=739.78,827.99
XS Rating Curve= 0
Exp/Cntr=.3,.1

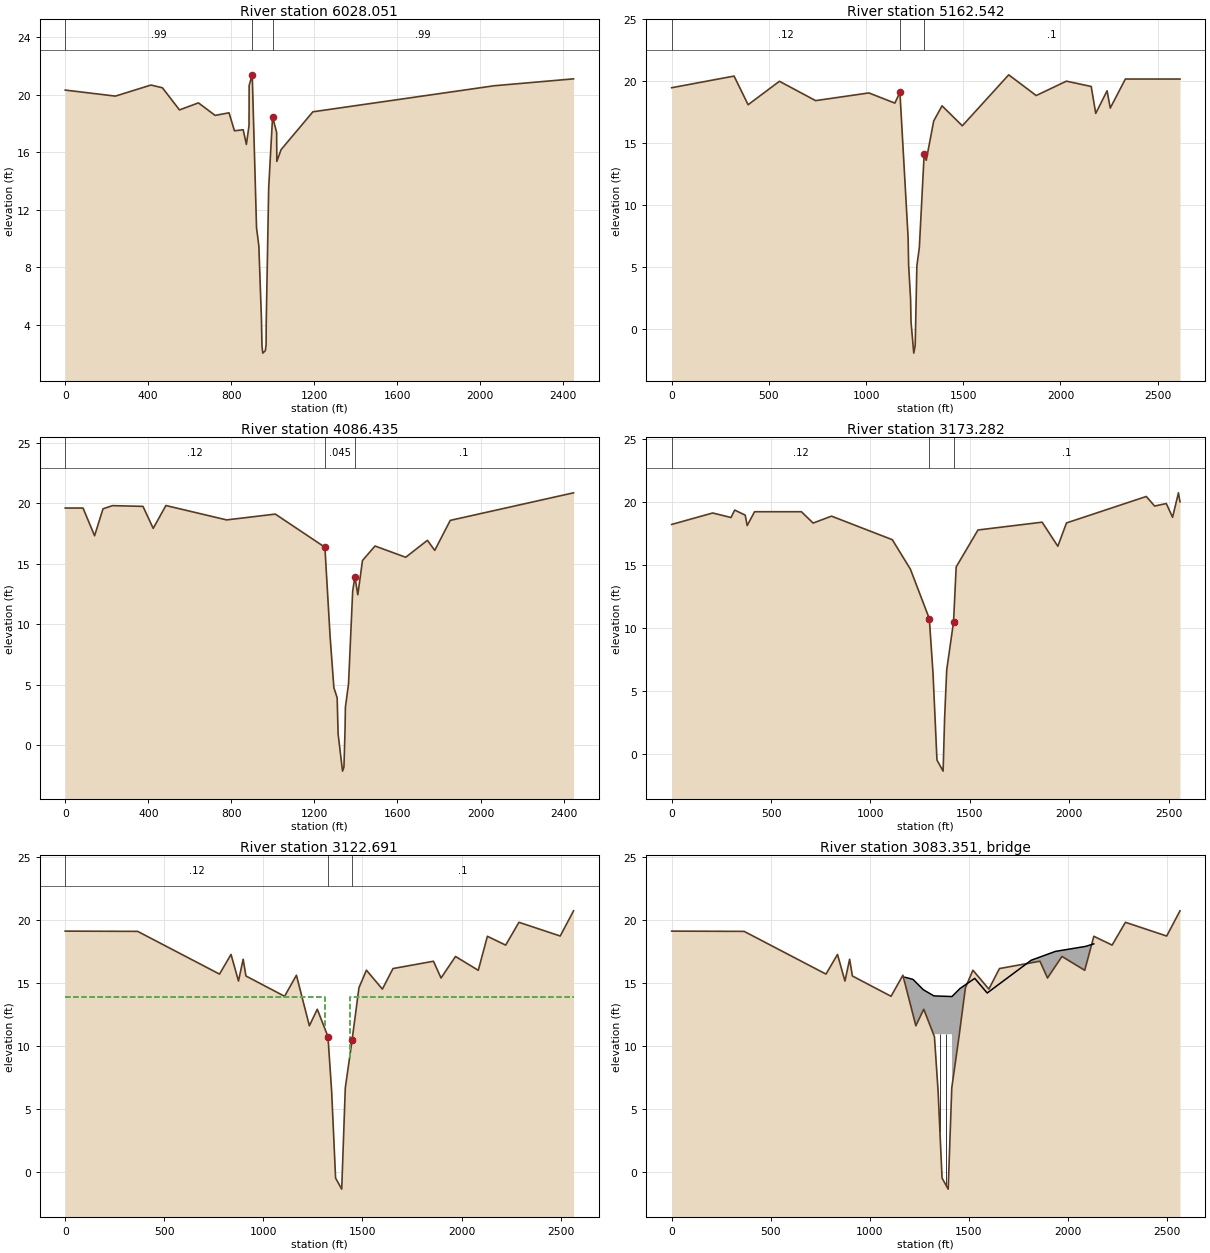
Type RM Length L Ch R = 1 ,6028.051,780.82,865.51,936.66
BEGIN DESCRIPTION:
434s8u - footbridge structure, not modeled
Bank Station offset =      4048
Manning's 'n' in channel increased from 0.04 of FIS study to 0.05 to account for roughness of footbridge.  The footbridge is not modeled as structure as we anticipate it unlikely to withstand a 100 yr flood.
END DESCRIPTION:
XS GIS Cut Line= 4
     3258309.673    13852485.485      3257618.93    13851928.879
       3257499.1     13851871.14     3256470.264    13850877.525
#Sta/Elev= 30
       0   20.32  242.02    19.9  413.27   20.67  468.56   20.48  550.91   18.94
  642.29   19.43  722.57   18.56  789.78   18.74  815.81   17.49  857.98   17.56
   873.4   16.54   886.1   17.85  886.71   20.64  901.63   21.38   922.3   10.75
  933.46    9.49  945.86    4.47  948.64     2.5  952.49    2.03  964.69     2.2
  968.33     2.6  969.11    4.19   980.9   13.52  999.61   18.46 1019.19   17.38
 1020.11   15.36 1040.69   16.18 1194.01   18.81 2068.06   20.62 2450.42    21.1
#Mann= 3 ,-1 , 0
       0     .99       0  901.63     .05       0  999.61     .99       0
Bank Sta=901.63,999.61
XS Rating Curve= 0
Exp/Cntr=.3,.1

Type RM Length L Ch R = 1 ,5162.542,1079.48,1076.11,1044.99
BEGIN DESCRIPTION:
434v9
Bank Station offset =      3755
END DESCRIPTION:
XS GIS Cut Line= 5
     3258553.304    13852327.126     3258407.125    13851973.862
     3258037.476    13851303.717     3258016.208    13851143.171
      3257322.97       13850037.
#Sta/Elev= 30
       0   19.48  321.01   20.42   393.3   18.11  554.44      20  740.38   18.44
 1014.68   19.06 1148.17   18.24 1174.25   19.11 1216.29     7.4 1219.07    5.17
 1229.07    2.44 1231.33      .6 1245.44   -1.92 1252.73   -1.31 1261.39    5.12
 1274.07    6.58 1298.94   14.13  1309.6   13.63 1348.04    16.8 1390.91   18.02
 1495.25   16.41  1733.9   20.52 1875.37   18.85 2030.79   20.01 2158.31   19.58
 2181.51   17.41 2239.97   19.23 2256.25   17.84 2334.02   20.18 2615.04   20.18
#Mann= 3 , 0 , 0
       0     .12       0 1174.25    .045       0 1298.94      .1       0
Bank Sta=1174.25,1298.94
XS Rating Curve= 0
Exp/Cntr=.3,.1

Type RM Length L Ch R = 1 ,4086.435,881.68,913.15,902.22
BEGIN DESCRIPTION:
434v10
Bank Station offset =      3665
END DESCRIPTION:
XS GIS Cut Line= 5
     3259299.919    13852196.723     3259272.013    13852071.314
     3259027.678    13850999.699     3258958.642     13850844.44
     3258598.784    13849857.778
#Sta/Elev= 30
       0   19.62   85.89   19.62  141.48   17.33  182.05   19.56  227.45   19.82
  374.52   19.76  423.79   17.94  484.82   19.83  777.07   18.64 1011.87   19.12
 1250.52   16.38 1275.77    8.94  1293.7    4.77 1309.54    3.93 1314.16     .94
 1335.44   -2.14 1342.23   -1.81 1347.42    1.23 1349.21    3.14 1364.31    5.08
  1384.2   12.74 1394.88   13.95 1409.01   12.45 1431.49   15.28  1491.8   16.48
 1639.61   15.55 1744.03   16.95 1779.47   16.12 1854.12    18.6 2447.75   20.88
#Mann= 3 , 0 , 0
       0     .12       0 1250.52    .045       0 1394.88      .1       0
Bank Sta=1250.52,1394.88
XS Rating Curve= 0
Exp/Cntr=.3,.1

Type RM Length L Ch R = 1 ,3173.282,48.76,50.59,52.86
BEGIN DESCRIPTION:
434s9u, Raccoon Drive.  XS 4/4.
Bank Station offset =      3634
END DESCRIPTION:
XS GIS Cut Line= 5
     3259584.756    13852120.037     3259639.532    13851780.424
     3259819.399    13850879.255     3259839.411    13850710.657
     3260077.742    13849611.285
#Sta/Elev= 30
       0   18.22   206.4   19.13  298.51   18.77  317.03   19.36  370.15   18.96
   379.7   18.13  417.12   19.23  652.69   19.23  711.72   18.33  804.19   18.88
 1110.13   17.01 1201.19   14.67  1296.4   10.74    1315    6.39 1334.85    -.48
 1365.74   -1.36 1373.43     2.9 1383.88    6.67 1418.19   10.48 1431.53   14.85
 1541.15   17.78 1863.93    18.4 1942.92   16.49 1986.63   18.34    2388   20.44
 2430.01   19.68 2488.72   19.88 2520.23   18.79 2549.83   20.73 2557.64   20.01
#Mann= 3 , 0 , 0
       0     .12       0  1296.4    .045       0 1418.19      .1       0
Bank Sta=1296.4,1418.19
XS Rating Curve= 0
Exp/Cntr=.5,.3

Type RM Length L Ch R = 1 ,3122.691,78.07,78.68,74.97
BEGIN DESCRIPTION:
Copy of 434s9u, Raccoon Drive.  XS 3/4.  Adjust elevations as needed.
Bank Station offset =      3605
END DESCRIPTION:
XS GIS Cut Line= 6
     3259628.577    13852152.902     3259716.219    13851665.394
     3259827.448    13851076.455     3259866.875    13850881.783
     3259892.392    13850711.889     3260132.518    13849638.673
#Sta/Elev= 30
       0   19.11  365.64   19.09  778.58    15.7   836.7   17.26  874.34   15.15
   897.9   16.88  911.98   15.55  1106.9   13.94 1166.65   15.61 1231.98    11.6
 1271.91   12.91  1325.8   10.74  1344.4    6.39 1364.25    -.48 1395.14   -1.36
 1413.28    6.67 1447.59   10.48 1482.23   14.62 1519.89   16.01 1600.44   14.51
  1653.9   16.14 1858.15   16.72  1896.4   15.39 1969.34    17.1 2084.24      16
 2130.15    18.7  2222.4      18  2289.5   19.81 2497.66   18.72 2564.85   20.72
#Mann= 3 , 0 , 0
       0     .12       0  1325.8    .045       0 1447.59      .1       0
#XS Ineff= 2 , 0
       0    1310   13.92    1435       0   13.92
Permanent Ineff=
       F       F
Bank Sta=1325.8,1447.59
XS Rating Curve= 0
Exp/Cntr=.5,.3

Type RM Length L Ch R = 3 ,3083.351,,,
BEGIN DESCRIPTION:
434s9- Raccoon Drive.
END DESCRIPTION:
Bridge Culvert--1,0,-1,-1, 0
Deck Dist Width WeirC Skew NumUp NumDn MinLoCord MaxHiCord MaxSubmerge Is_Ogee
17,46,2.6,0, 14, 14, , , .95, 0, 0,0,,
 1177.05 1217.78 1269.66 1323.46 1323.46 1414.21 1414.21 1454.92 1529.14    1592
    1814    1936    2089    2130
   15.45   15.28   14.46   13.97   13.97   13.92   13.92   14.56   15.36    14.2
    16.8    17.5    17.9    18.1
       0       0       0       0   10.93   10.93       0       0       0
                                
 1170.05 1210.78 1262.66 1316.46 1316.46 1407.21 1407.21 1447.92 1522.14    1585
    1807    1929    2082    2123
   15.45   15.28   14.46   13.97   13.97   13.92   13.92   14.56   15.36    14.2
    16.8    17.5    17.9    18.1
       0       0       0       0   10.93   10.93       0       0       0       0
                                
Pier Skew, UpSta & Num, DnSta & Num=  ,1353.79, 4 ,1346.79, 4 , 3 , 3 , 0 ,0,
    1.35    1.35     1.5     1.5
      -5    9.43    9.43      11
    1.35    1.35     1.5     1.5
      -5    9.43    9.43      11
Pier Skew, UpSta & Num, DnSta & Num=  ,1383.96, 4 ,1376.96, 4 , 3 , 3 , 0 ,0,
    1.35    1.35     1.5     1.5
      -5    9.43    9.43      11
    1.35    1.35     1.5     1.5
      -5    9.43    9.43      11
BR Coef=-1 , 0 , 0 ,, 0 ,,,.8,0,,1,
WSPro=,,,, 1 ,,,, 0 ,,,, 0 ,,,,-1 ,-1 ,-1 , 0 , 0 , 0 , 0 , 0
BC Design=,, 0 ,, 0 ,,,,,,

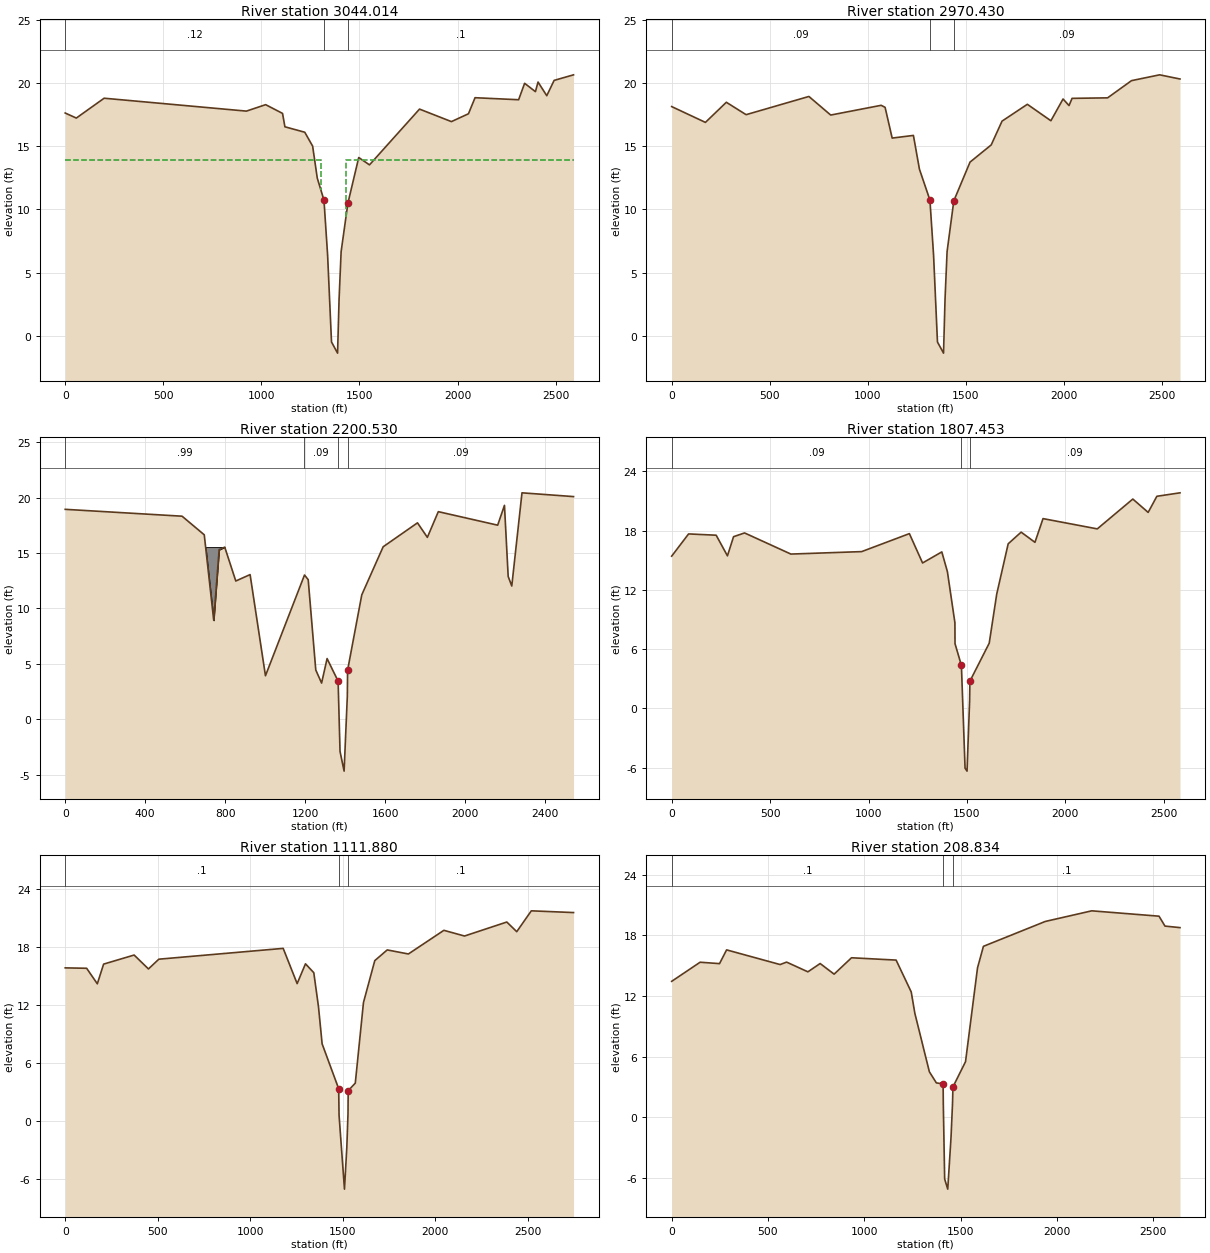
Type RM Length L Ch R = 1 ,3044.014,76.54,73.58,73.58
BEGIN DESCRIPTION:
Copy of 434s9u, Raccoon Drive.  XS 2/4.  Adjust elevations as needed.
Bank Station offset =      3612
END DESCRIPTION:
XS GIS Cut Line= 6
     3259688.831    13852152.902     3259820.294    13851517.498
      3259898.91    13851090.008     3259955.586    13850831.267
     3259963.854    13850726.675     3260214.682    13849616.763
#Sta/Elev= 30
       0   17.63   56.63   17.23  198.42    18.8  923.61   17.78 1021.74   18.29
 1107.82    17.6 1119.97   16.54 1221.23   16.11 1261.32   15.01 1284.96   12.48
 1319.05   10.74 1337.65    6.39  1357.5    -.48 1388.39   -1.36 1396.08     2.9
 1406.53    6.67 1440.84   10.48 1496.24   14.11 1551.16   13.53 1806.17   17.94
 1968.72   16.95  2055.6   17.57 2089.21   18.84 2311.29   18.68 2341.95   19.98
 2396.98   19.32 2410.32   20.08 2454.78      19 2492.33   20.21 2591.23   20.65
#Mann= 3 , 0 , 0
       0     .12       0 1319.05    .045       0 1440.84      .1       0
#XS Ineff= 2 , 0
       0    1303   13.92    1431       0   13.92
Permanent Ineff=
       F       F
Bank Sta=1319.05,1440.84
XS Rating Curve= 0
Exp/Cntr=.5,.3

Type RM Length L Ch R = 1 ,2970.430,781.75,769.9,733.84
BEGIN DESCRIPTION:
Copy of 434s9u, Raccoon Drive.  XS 1/4.  Adjust elevations as needed.  Low LiDAR points in near ROB removed upon careful review of aerial and field reconnaissance data.
Bank Station offset =      3614
END DESCRIPTION:
XS GIS Cut Line= 5
     3259754.562     13852158.38      3259896.98    13851473.677
     3260020.231    13850902.665     3260040.244    13850734.067
     3260280.414     13849622.24
#Sta/Elev= 30
       0   18.13     172   16.88  278.61   18.47   379.4   17.49  699.36   18.93
  810.54   17.46 1067.73   18.23 1087.74   18.07 1123.83   15.64 1232.09   15.85
 1262.82   13.18 1316.22   10.74 1334.82    6.39 1354.67    -.48 1385.56   -1.36
 1393.25     2.9  1403.7    6.67 1438.01   10.68 1520.66   13.74  1628.6    15.1
  1683.8   16.98 1812.81   18.31 1932.77   17.01 1994.76   18.73 2025.28   18.21
 2040.64   18.78  2221.8   18.82 2343.64   20.18 2487.05   20.64 2590.77   20.31
#Mann= 3 , 0 , 0
       0     .09       0 1316.22     .04       0 1438.01     .09       0
Bank Sta=1316.22,1438.01
XS Rating Curve= 0
Exp/Cntr=.3,.1

Type RM Length L Ch R = 1 ,2200.530,418.38,393.08,367.7
BEGIN DESCRIPTION:
434v11
Bank Station offset =      3449
Manning's n set = 0.99 in low area on near lob.  This area will not convey flow from Cary effectively.  It should not be blocked, as it will likely be inundated.
END DESCRIPTION:
XS GIS Cut Line= 5
     3260752.617    13852394.681       3260782.5     13851946.44
     3260746.046    13850929.912     3260727.923    13850821.057
     3260636.343    13849574.102
#Sta/Elev= 30
       0   18.95 584.234   18.33   695.1   16.65 742.494    8.93 769.476    15.3
 797.473   15.54 852.713   12.48 924.212   13.061001.023    3.931196.142   13.02
1214.666    12.61252.523    4.45 1281.59    3.271309.103    5.481364.136    3.44
1373.798    -2.9 1394.11   -4.681410.235    2.081411.628    4.431482.444   11.23
1589.347   15.571760.962   17.731810.342   16.421865.007   18.742161.815   17.52
2195.709   19.312214.323   12.89 2232.29   12.032283.314   20.442540.963    20.1
#Mann= 4 ,-1 , 0
       0     .99       01196.142     .09       01364.136     .04       0
1411.628     .09       0
#Block Obstruct= 2 , 0
       0 797.473   15.542195.709       0   19.31
Bank Sta=1364.136,1411.628
XS Rating Curve= 0
Skew Angle= 26
Exp/Cntr=.3,.1

Type RM Length L Ch R = 1 ,1807.453,608.22,695.57,651.95
BEGIN DESCRIPTION:
434v12
Bank Station offset =      3492
END DESCRIPTION:
XS GIS Cut Line= 5
     3261270.585    13852105.814     3261086.732    13850678.858
     3261023.083    13850611.496     3260832.304    13849715.191
     3260794.703    13849586.284
#Sta/Elev= 30
       0   15.41   85.97   17.66  226.05   17.53  283.32   15.44  314.29   17.38
  370.32   17.76  605.67   15.62  965.18   15.87 1207.48   17.69 1274.47   14.72
 1372.25   15.84 1400.62   13.84 1438.75    8.67 1439.29    6.55 1471.79    4.35
 1490.29   -6.05 1500.29   -6.35 1513.49     .81 1514.85    2.75    1613     6.6
 1651.12   11.57 1709.34   16.66 1775.15   17.84 1845.34   16.81  1886.3   19.21
 2161.92   18.17 2342.48   21.19 2420.36   19.84  2464.6   21.47 2582.09   21.82
#Mann= 3 , 0 , 0
       0     .09       0 1471.79     .04       0 1514.85     .09       0
Bank Sta=1471.79,1514.85
XS Rating Curve= 0
Exp/Cntr=.3,.1

Type RM Length L Ch R = 1 ,1111.880,815.98,903.05,909.72
BEGIN DESCRIPTION:
434v13
Bank Station offset =      3491
END DESCRIPTION:
XS GIS Cut Line= 4
     3261645.727    13852088.447     3261650.221    13850636.193
      3261596.98    13850543.417     3261504.539    13849358.805
#Sta/Elev= 30
       0   15.83  115.79   15.79  173.63   14.18  207.52   16.22  372.55   17.16
   449.9   15.72  506.12   16.73 1178.15   17.85 1253.64    14.2 1298.64   16.25
 1343.64   15.33  1368.9   11.81 1388.64    7.96 1478.12    3.31 1480.12     .56
 1509.42   -7.09 1522.12   -2.74 1528.52     .76 1529.42    3.11 1567.86    3.89
 1612.07   12.24 1673.18   16.58 1740.47   17.69 1854.87   17.27  2046.7   19.72
 2158.23   19.13 2386.82   20.58  2440.5   19.58 2519.27   21.74 2747.44   21.56
#Mann= 3 , 0 , 0
       0      .1       0 1478.12     .04       0 1529.42      .1       0
Bank Sta=1478.12,1529.42
XS Rating Curve= 0
Exp/Cntr=.3,.1

Type RM Length L Ch R = 1 ,208.834 ,157.2,208.84,316.31
BEGIN DESCRIPTION:
434v14
Bank Station offset =      3567
END DESCRIPTION:
XS GIS Cut Line= 4
     3262248.131    13852013.147       3262465.4    13850654.872
     3262478.346    13850530.868     3262709.346     13849415.28
#Sta/Elev= 30
       0   13.44  147.75   15.33  248.51   15.19  285.18   16.55  563.04    15.1
  596.79   15.34  707.37   14.38     771    15.2  843.51   14.15  933.87   15.77
 1165.45   15.54  1243.9   12.39 1262.74   10.28 1338.09     4.5 1374.48     3.4
 1409.48     3.3 1410.48     1.3 1417.48    -6.1 1433.48    -7.1 1450.48      -2
 1458.48    1.45 1460.48       3 1525.85     5.5  1588.1   14.77 1618.73    16.9
 1940.05   19.36 2181.38   20.41 2530.58   19.88 2561.49    18.9 2639.47   18.75
#Mann= 3 , 0 , 0
       0      .1       0 1409.48     .04       0 1460.48      .1       0
Bank Sta=1409.48,1460.48
XS Rating Curve= 0
Exp/Cntr=.3,.1

Chan Stop Cuts=-1